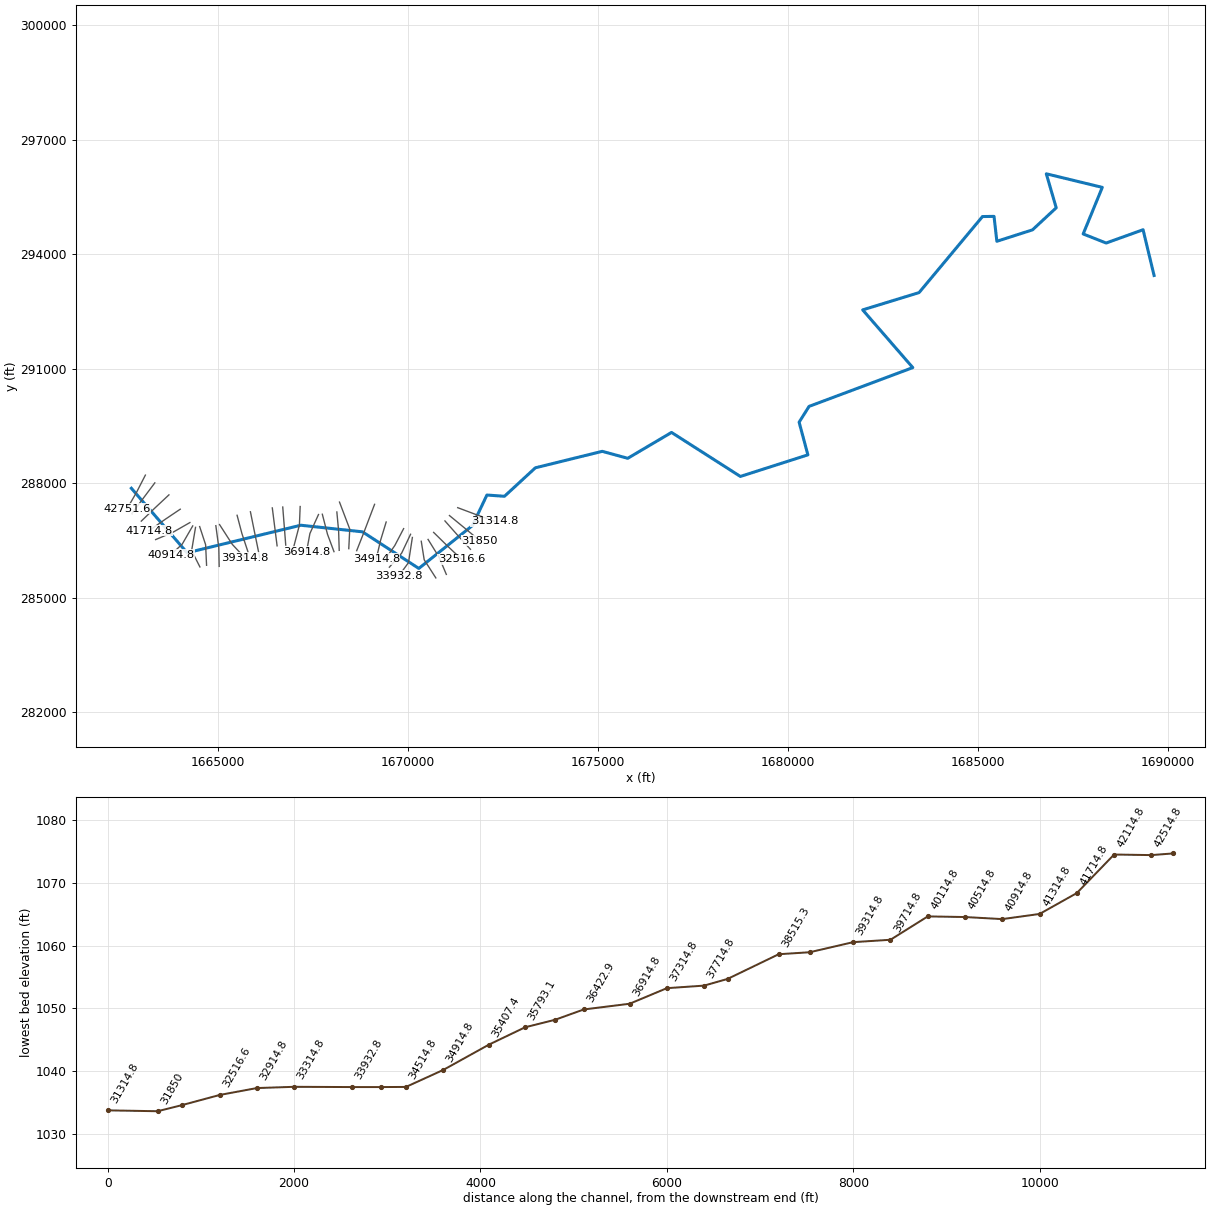
--- SalemFk.prj (project) ---

Proj Title=SalemFk
Current Plan=p01
Default Exp/Contr=0,0
English Units
Geom File=g01
Flow File=f01
Plan File=p01
BEGIN DESCRIPTION:
END DESCRIPTION:
DSS Export Rating Curves= 0
DSS Export Rating Curve Sorted= 0
DSS Export Volume Flow Curves= 0
DXF OffsetX= 0
DXF OffsetY= 0
DXF ScaleX= 0
DXF ScaleY= 0

--- SalemFk.p01 (plan) ---

Plan Title=Floodplain
Program Version=4.00
Geom File=g01
Flow File=f01
K Sum by GR=0
Std Step Tol=0.01
Critical Tol=0.01
Num of Std Step Trials=20
Max Error Tol=0.3
Flow Tol Ratio=0.001
Split Flow NTrial=30
Split Flow Tol=0.02
Split Flow Ratio=0.02
Log Output Level=0
Friction Slope Method=1
Unsteady Friction Slope Method=2
Unsteady Bridges Friction Slope Method=1
Global Log Level=0
CheckData=False
Run HTab=0
Run UNet=0
Run PostProcess=0
UNET Theta=0
UNET Theta Warmup=0
UNET ZTol=0
UNET ZSATol=0
UNET MxIter=0
UNET MaxInSteps=0
UNET DtIC=0
UNET DtMin=0
UNET MaxCRTS=0
UNET WFStab=0
UNET SFStab=0
UNET WFX=0
UNET SFX=0
UNET DSS MLevel=0
UNET DZMax Abort=0
UNET Convert EG Bridges=0
UNET Use Existing IB Tables=0
UNET Froude Limit=0
UNET Froude Power=0
Write IC File=0
Echo Input=False
Echo Output=False
Write Detailed=0

--- SalemFk.f01 (steady flow) ---

Flow Title=NFF Regression Equation
Program Version=4.00
Number of Profiles= 1
Profile Names=P100yr
River Rch & RM=SalemFk,Main            ,42751.6
 739.018
River Rch & RM=SalemFk,Main            ,41714.8
772.2763
River Rch & RM=SalemFk,Main            ,40514.8
843.7612
River Rch & RM=SalemFk,Main            ,38848.8
 885.469
River Rch & RM=SalemFk,Main            ,37967
975.6216
River Rch & RM=SalemFk,Main            ,35793.1
1020.309
River Rch & RM=SalemFk,Main            ,35407.4
1595.617
River Rch & RM=SalemFk,Main            ,33932.8
1615.486
River Rch & RM=SalemFk,Main            ,33314.8
2338.112
River Rch & RM=SalemFk,Main            ,30114.8
2559.603
River Rch & RM=SalemFk,Main            ,24956.9
2792.582
River Rch & RM=SalemFk,Main            ,24391.8
3182.552
River Rch & RM=SalemFk,Main            ,20914.8
3435.571
River Rch & RM=SalemFk,Main            ,342.9
3814.255
River Rch & RM=SalemFk,Main            ,47.6
4642.262
Boundary for River Rch & Prof#=SalemFk,Main            , 1
Up Type= 0
Dn Type= 3
Dn Slope=0.002071
DSS Import GetInterval= 0
DSS Import GetPeak= 0
DSS Import FillOption= 0

--- SalemFk.g01 (geometry) ---

Geom Title=USGS 3m DEM
Program Version=4.00

River Reach=SalemFk         ,Main
Reach XY= 30
     1662715.695      287865.722     1664183.414      286175.556
     1667178.037      286896.993     1668800.053      286724.483
     1670284.688       285764.64     1671697.515      286889.324
     1672076.754      287688.582      1672540.09      287655.747
     1673353.374       288401.87     1675114.463      288833.782
     1675784.927      288650.959     1676938.684      289328.827
     1678751.031      288175.414     1680528.135      288741.363
     1680297.793      289597.923     1680559.921      290011.548
     1683291.007      291027.864     1681971.282      292540.773
     1683455.713      292993.616     1685125.976      294986.654
     1685429.575      294991.407     1685504.519      294338.782
     1686442.812       294638.06     1687067.437      295216.135
     1686806.076      296107.399     1688280.253      295751.525
     1687777.291      294530.655     1688381.632      294292.879
     1689354.189      294640.871     1689643.689      293442.676

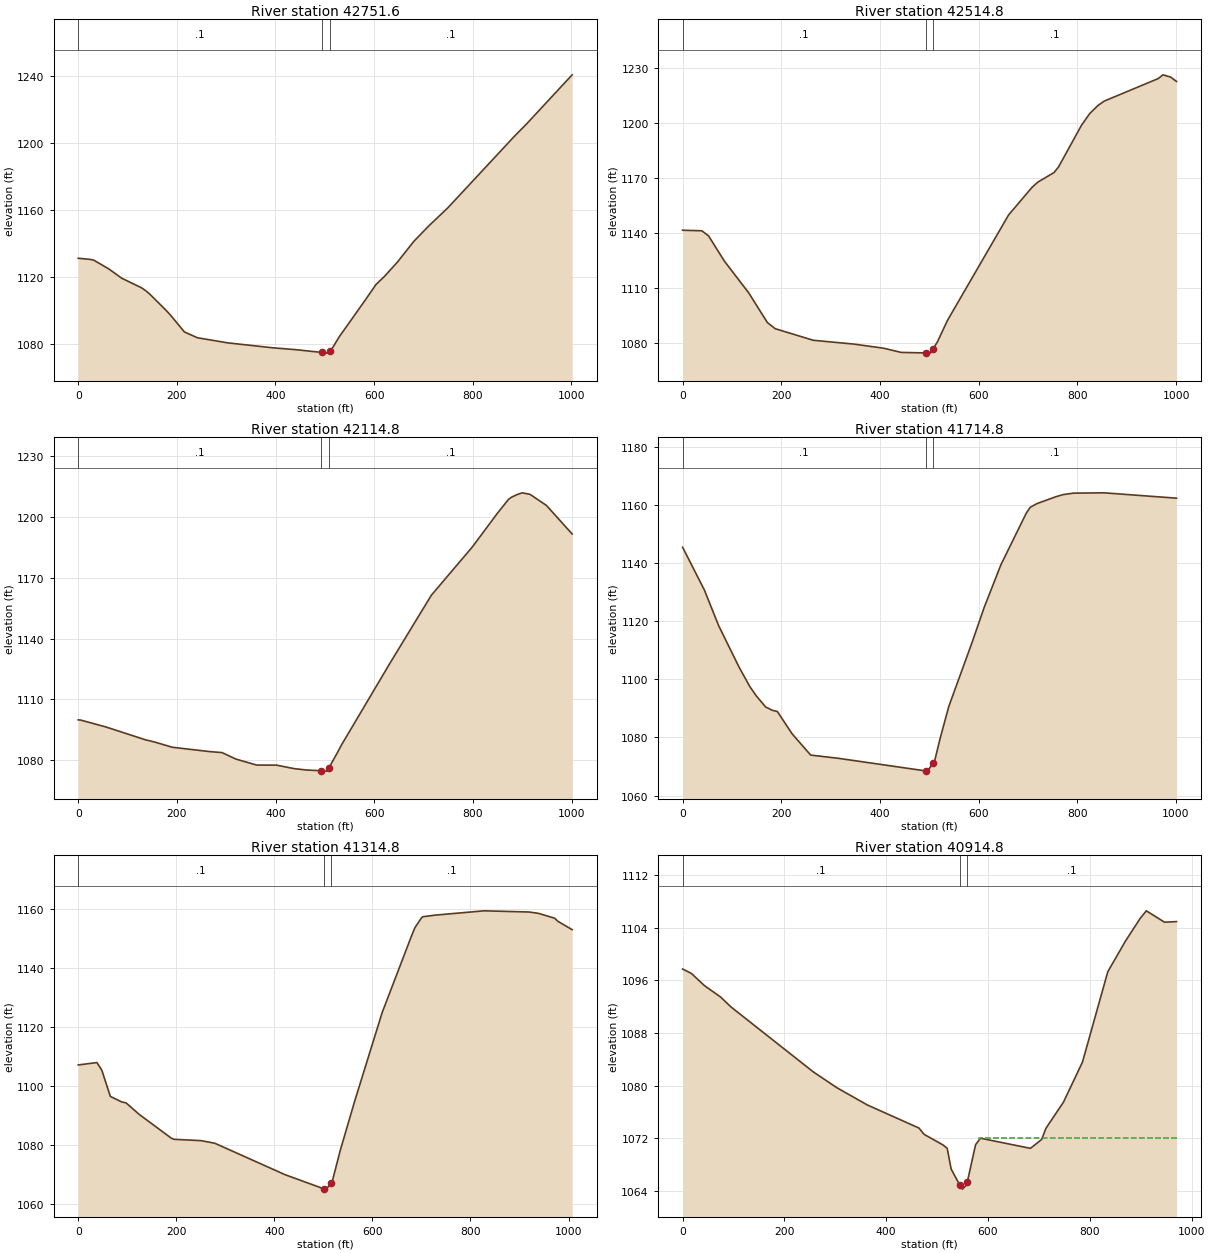
Type RM Length L Ch R = 1 ,42751.6 ,240.701,236.729,233.94
XS GIS Cut Line= 3
     1663084.439      288210.434     1662855.316      287765.609
      1662604.39      287331.714
#Sta/Elev= 30
       0 1131.23    25.3  1130.5    31.4 1130.11    61.8 1124.91    88.1 1119.36
   128.6 1113.59   138.3 1111.59   145.6 1109.72     179 1099.96   188.3 1096.94
   215.3 1087.35   241.7 1083.88   303.1 1080.85   395.1 1077.88   439.3 1076.84
   494.6 1075.12   505.5 1074.73   509.6 1075.88   516.3 1078.12   528.7  1084.2
   581.6 1106.15   603.8 1115.58   621.2 1120.47   647.1 1128.88   680.9  1141.4
   711.1 1150.55   749.4 1161.22   882.5 1203.24   909.4 1211.29  1001.6 1240.45
#Mann= 3 , 0 , 0
       0      .1       0   494.6    .045       0   509.6      .1       0
Bank Sta=494.6,509.6
XS Rating Curve= 0 ,0
Exp/Cntr=0.3,0.1

Type RM Length L Ch R = 1 ,42514.8 ,403.934,400,396.302
XS GIS Cut Line= 3
     1663333.476      288007.503     1663032.121      287607.891
      1662732.28      287207.148
#Sta/Elev= 30
       0 1141.52    39.1 1141.21    52.6 1138.43    84.7 1124.66   134.1  1107.3
   171.8 1091.15   187.7 1087.79   264.8 1081.47   347.5 1079.38   407.9 1077.12
   442.8 1074.85     493 1074.56   500.5 1074.46   502.8 1074.65     508 1076.92
   516.4 1080.59   536.7 1092.27   660.7 1149.87   708.2 1164.93   719.9 1167.76
   752.7 1172.99   761.9 1176.06   808.1 1198.66   825.1 1205.19     842 1209.64
   854.6 1211.99   963.7 1224.24   973.4 1226.31   989.3 1225.05    1001  1222.7
#Mann= 3 , 0 , 0
       0      .1       0     493    .045       0     508      .1       0
Bank Sta=493,508
XS Rating Curve= 0 ,0
Exp/Cntr=0.3,0.1

Type RM Length L Ch R = 1 ,42114.8 ,403.583,400,396.538
XS GIS Cut Line= 3
     1663704.802      287692.503     1663338.564      287351.389
     1662977.171      287005.041
#Sta/Elev= 30
       0 1099.86     4.9 1099.76    55.9 1096.37   135.8 1090.05   156.3 1088.82
   190.7 1086.33   266.7 1084.19   291.4  1083.7   319.5 1080.51   361.6 1077.54
   401.9 1077.51   437.3  1075.8   461.8 1075.12     493 1074.73   504.3 1074.55
     508 1076.13     526 1083.99   533.2 1087.32   630.4 1127.26   715.7 1161.39
     799  1185.3   849.7  1201.9   872.2 1208.74   878.3 1209.82   890.7 1211.22
   899.9 1211.96   914.9 1211.27     917    1211   948.9 1205.75  1001.1 1191.63
#Mann= 3 , 0 , 0
       0      .1       0     493    .045       0     508      .1       0
Bank Sta=493,508
XS Rating Curve= 0 ,0
Exp/Cntr=0.3,0.1

Type RM Length L Ch R = 1 ,41714.8 ,401.75,400,395.151
XS GIS Cut Line= 3
     1664002.205       287316.92     1663586.582      287038.103
     1663176.285       286751.04
#Sta/Elev= 30
       0 1145.39      44 1130.75    73.3 1118.34   114.5 1104.16   136.3 1097.46
   149.4 1094.28   168.3 1090.47   181.7 1089.34   192.2 1088.89   221.9 1081.25
   259.6 1073.92   316.5 1072.79     493 1068.47   495.8  1068.4     508 1071.05
   508.8 1071.09   511.6 1072.41   521.8  1079.5   539.5  1090.6   587.2 1112.87
   611.1 1124.61   645.2 1139.37   696.9 1157.21   704.9 1159.17   718.3 1160.41
   756.7 1162.79   771.4 1163.51   792.3 1164.01   854.2 1164.12  1001.2 1162.28
#Mann= 3 , 0 , 0
       0      .1       0     493    .045       0     508      .1       0
Bank Sta=493,508
XS Rating Curve= 0 ,0
Exp/Cntr=0.3,0.1

Type RM Length L Ch R = 1 ,41314.8 ,386.887,400,407.824
XS GIS Cut Line= 3
     1664256.582      286966.669     1663814.921      286715.119
     1663355.221      286520.684
#Sta/Elev= 30
       0  1107.1    38.2  1107.9    48.1 1105.31    65.5 1096.45    89.1 1094.54
    97.4 1094.27   124.6 1090.33   189.2 1082.39   194.9 1081.93   250.8 1081.47
   278.6 1080.59   421.7 1069.96   500.8 1065.17   506.1 1065.06   515.8 1067.21
   518.2 1067.75   534.7 1078.32     564 1094.92   619.9 1124.83   680.4 1151.04
   686.8 1153.59   699.9 1156.85   702.8 1157.27   728.5 1157.82   827.8 1159.27
   919.7 1158.87   938.7 1158.41   971.9 1156.76     978 1155.75  1007.4  1152.9
#Mann= 3 , 0 , 0
       0      .1       0   500.8    .045       0   515.8      .1       0
Bank Sta=500.8,515.8
XS Rating Curve= 0 ,0
Exp/Cntr=0.3,0.1

Type RM Length L Ch R = 1 ,40914.8 ,395.152,400,430.007
XS GIS Cut Line= 3
     1664331.231      286878.554     1664054.544      286400.914
     1663746.865      286117.586
#Sta/Elev= 30
       0 1097.74    17.2 1097.08    42.8 1095.22    74.8 1093.47    95.2 1091.96
     257 1082.07   303.4 1079.66   362.9 1077.05   464.2 1073.54   474.6 1072.57
   511.4 1070.97   519.8 1070.45   527.5 1067.31   544.5 1064.85   549.6 1064.24
   558.1  1064.9   559.5  1065.4   575.6 1071.01   585.1 1071.99   683.3 1070.45
   705.4  1071.8   713.6 1073.48   748.3 1077.49   785.5 1083.57   835.3 1097.33
   869.7 1101.96     899 1105.46     911  1106.6   946.7 1104.87   970.3 1104.96
#Mann= 3 , 0 , 0
       0      .1       0   544.5    .045       0   559.5      .1       0
#XS Ineff= 2 , 0
                          581.93         1071.99
Permanent Ineff=
       F       F
Bank Sta=544.5,559.5
XS Rating Curve= 0 ,0
Exp/Cntr=0.3,0.1

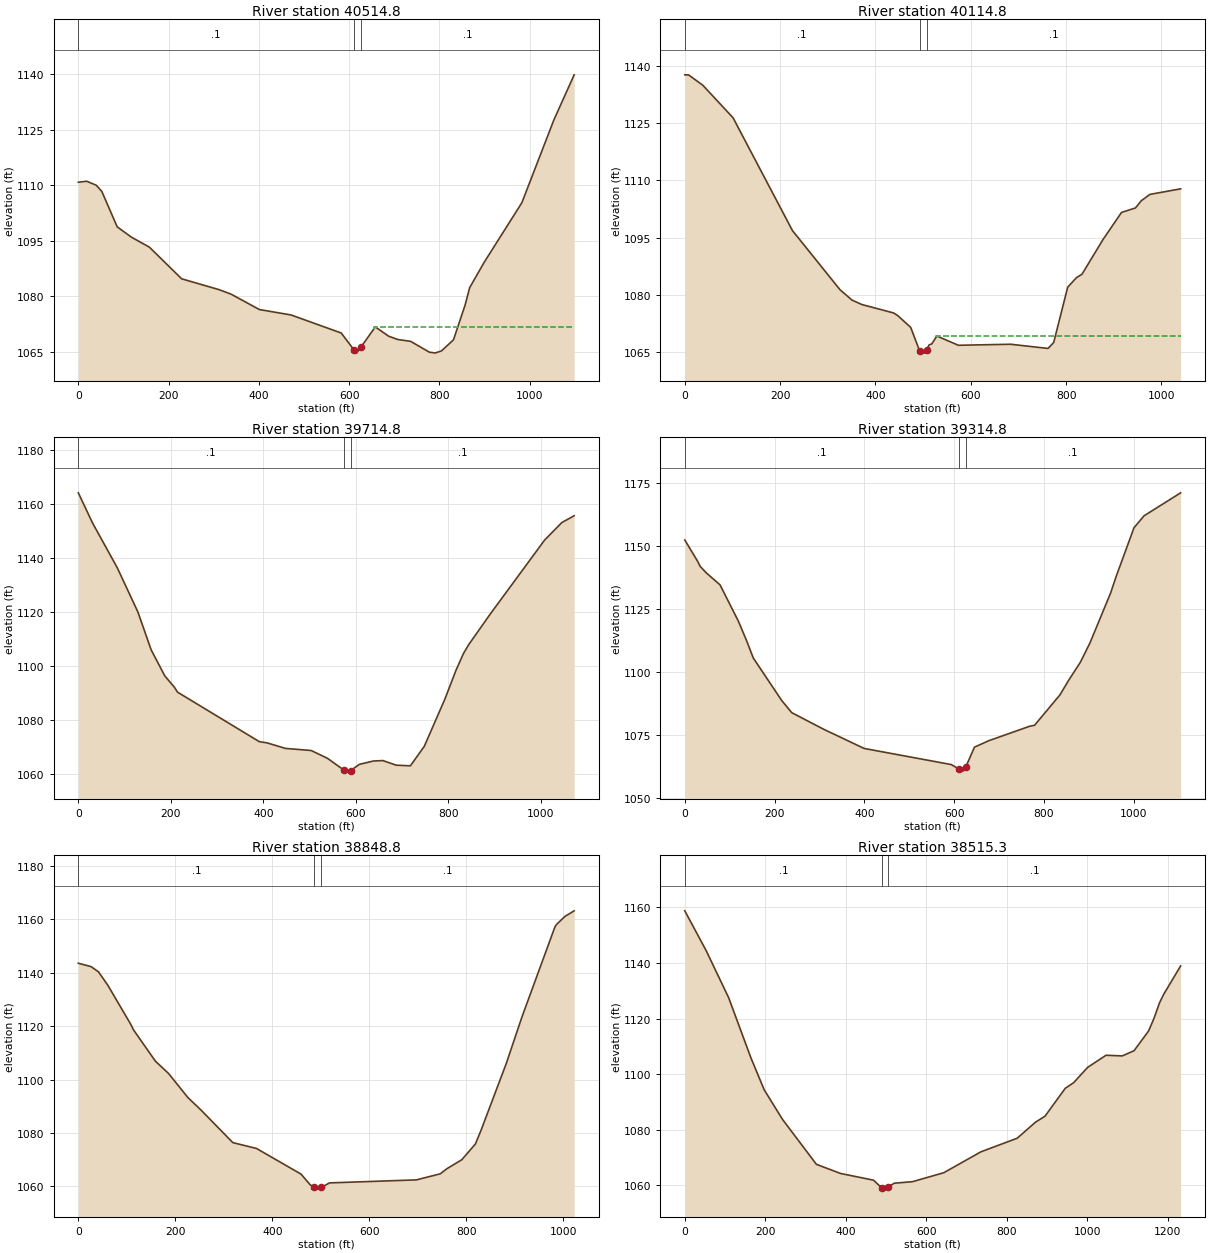
Type RM Length L Ch R = 1 ,40514.8 ,387.207,400,389.853
XS GIS Cut Line= 3
     1664405.168      286841.401     1664302.758      286231.831
     1664520.568      285803.841
#Sta/Elev= 30
       0 1110.77    18.6 1111.04    39.6 1109.97      52  1108.3    86.1 1098.71
   117.5 1095.93   157.4 1093.22   228.9 1084.66   311.5 1081.74   338.4 1080.51
   401.1 1076.35   471.2 1074.89   582.3 1070.01   610.6 1065.45   616.1 1064.57
   625.6 1066.12   657.8 1071.66   687.4 1069.15   707.2 1068.26     736 1067.76
   777.7 1064.82   790.6 1064.61   804.3 1065.16     831 1068.17   856.8  1077.6
   866.9 1082.28   898.8 1089.09   982.5 1105.24  1053.5 1127.65  1098.3 1139.81
#Mann= 3 , 0 , 0
       0      .1       0   610.6    .045       0   625.6      .1       0
#XS Ineff= 2 , 0
                          654.74         1071.68
Permanent Ineff=
       F       F
Bank Sta=610.6,625.6
XS Rating Curve= 0 ,0
Exp/Cntr=0.3,0.1

Type RM Length L Ch R = 1 ,40114.8 ,404.804,400,399.076
XS GIS Cut Line= 3
      1664513.99      286861.824     1664670.585      286387.105
     1664695.761      285847.361
#Sta/Elev= 30
       0 1137.68     7.9 1137.67      38 1134.93   101.3  1126.4   225.8 1096.83
   325.5 1081.32   350.6  1078.6   371.4 1077.42   438.1 1075.21   446.5 1074.54
   473.9 1071.43   492.4 1065.35   504.1 1064.67   507.4 1065.52   512.4 1066.81
   518.2  1067.1   528.8 1069.16     574 1066.73   683.6    1067     762  1065.9
   773.9 1067.45   803.3 1081.97   821.7 1084.47   833.3 1085.37   877.4 1094.48
   916.2 1101.58   945.4 1102.75   957.6 1104.64   975.8 1106.31  1040.2 1107.77
#Mann= 3 , 0 , 0
       0      .1       0   492.4    .045       0   507.4      .1       0
#XS Ineff= 2 , 0
                          527.19         1069.04
Permanent Ineff=
       F       F
Bank Sta=492.4,507.4
XS Rating Curve= 0 ,0
Exp/Cntr=0.3,0.1

Type RM Length L Ch R = 1 ,39714.8 ,390.167,400,416.652
XS GIS Cut Line= 3
     1664939.985      286885.079     1665018.208      286309.054
     1665027.699      285818.708
#Sta/Elev= 30
       0 1164.28    30.8 1153.06    84.1 1136.48   128.6  1120.1   157.4 1105.98
   186.9  1096.3   207.8 1092.07   214.4 1090.27   391.3 1071.87   408.1 1071.43
   447.8 1069.37   503.2  1068.6   538.4 1065.71   573.8 1061.36     587 1060.94
   588.8 1061.17   607.4 1063.45   638.1  1064.7   658.3 1064.86     687 1063.15
   717.7 1062.91   747.7 1070.12   792.7 1087.86   816.4 1098.43   832.4  1104.6
   843.8 1107.91   890.1 1119.21  1007.9 1146.75    1045 1153.23  1071.7 1155.78
#Mann= 3 , 0 , 0
       0      .1       0   573.8    .045       0   588.8      .1       0
Bank Sta=573.8,588.8
XS Rating Curve= 0 ,0
Exp/Cntr=0.3,0.1

Type RM Length L Ch R = 1 ,39314.8 ,473.867,466.027,454.772
XS GIS Cut Line= 3
     1665037.665      286914.016     1665373.574      286395.105
     1665706.008      286040.468
#Sta/Elev= 30
       0  1152.5    27.7 1144.31    34.4 1141.99    48.2 1139.37    78.4 1134.68
   119.3 1120.23   137.1 1112.68   152.6 1105.54   215.7 1088.68   238.1 1083.83
   309.2 1077.22   399.4 1069.58   593.5 1063.17   610.6 1061.37   619.2 1060.56
   622.9 1061.04   625.6 1062.15   645.1 1070.09   677.1 1072.67   768.3 1078.43
   778.8 1078.78   835.1 1090.81   855.2 1096.79   880.8 1103.83   902.2 1111.51
   948.4 1131.46   960.6 1137.98  1000.4 1157.39  1022.8 1162.13  1104.2 1171.27
#Mann= 3 , 0 , 0
       0      .1       0   610.6    .045       0   625.6      .1       0
Bank Sta=610.6,625.6
XS Rating Curve= 0 ,0
Exp/Cntr=0.3,0.1

Type RM Length L Ch R = 1 ,38848.8 ,334.896,333.473,330.809
XS GIS Cut Line= 3
     1665499.552      287157.537     1665625.841      286681.416
     1665792.921      286178.278
#Sta/Elev= 30
       0 1143.59    26.2 1142.32    41.7 1140.34    60.8 1135.35   107.6 1120.87
   113.9 1118.59     159 1106.89   186.2 1102.26   225.9 1093.28   253.1 1088.57
   318.7 1076.37   367.5 1074.19   459.5 1064.56   478.4 1060.52   486.5 1059.82
   495.2 1058.95   501.5  1059.6     518 1061.28   697.6 1062.42   746.5 1064.69
   760.5 1066.63   790.9 1069.96   818.9 1075.83     831 1081.16   882.8 1106.08
   914.9 1123.39   983.2 1157.27   987.1 1158.25  1003.9 1161.15  1022.7 1163.22
#Mann= 3 , 0 , 0
       0      .1       0   486.5    .045       0   501.5      .1       0
Bank Sta=486.5,501.5
XS Rating Curve= 0 ,0
Exp/Cntr=0.3,0.1

Type RM Length L Ch R = 1 ,38515.3 ,550.022,548.363,546.654
XS GIS Cut Line= 3
     1665850.473      287249.763     1665949.935      286759.246
     1666097.122      286042.519
#Sta/Elev= 30
       0 1158.74    52.9 1144.48     109 1127.49   164.1 1105.94   197.3 1094.36
   243.1 1083.66   327.1 1067.55   387.2 1064.26     469 1061.85   490.5 1058.94
   492.8 1058.63   505.5 1059.42   520.6 1060.76   565.9 1061.31   643.8 1064.54
     736 1072.06   826.1 1076.94   871.6 1082.72   895.2 1084.87   945.5  1094.9
   966.4 1096.93  1001.2 1102.44  1046.9 1106.79  1087.1 1106.55  1116.4 1108.41
  1152.6 1115.51  1165.6  1119.9    1180 1125.71  1190.2 1128.73  1232.2 1138.92
#Mann= 3 , 0 , 0
       0      .1       0   490.5    .045       0   505.5      .1       0
Bank Sta=490.5,505.5
XS Rating Curve= 0 ,0
Exp/Cntr=0.3,0.1

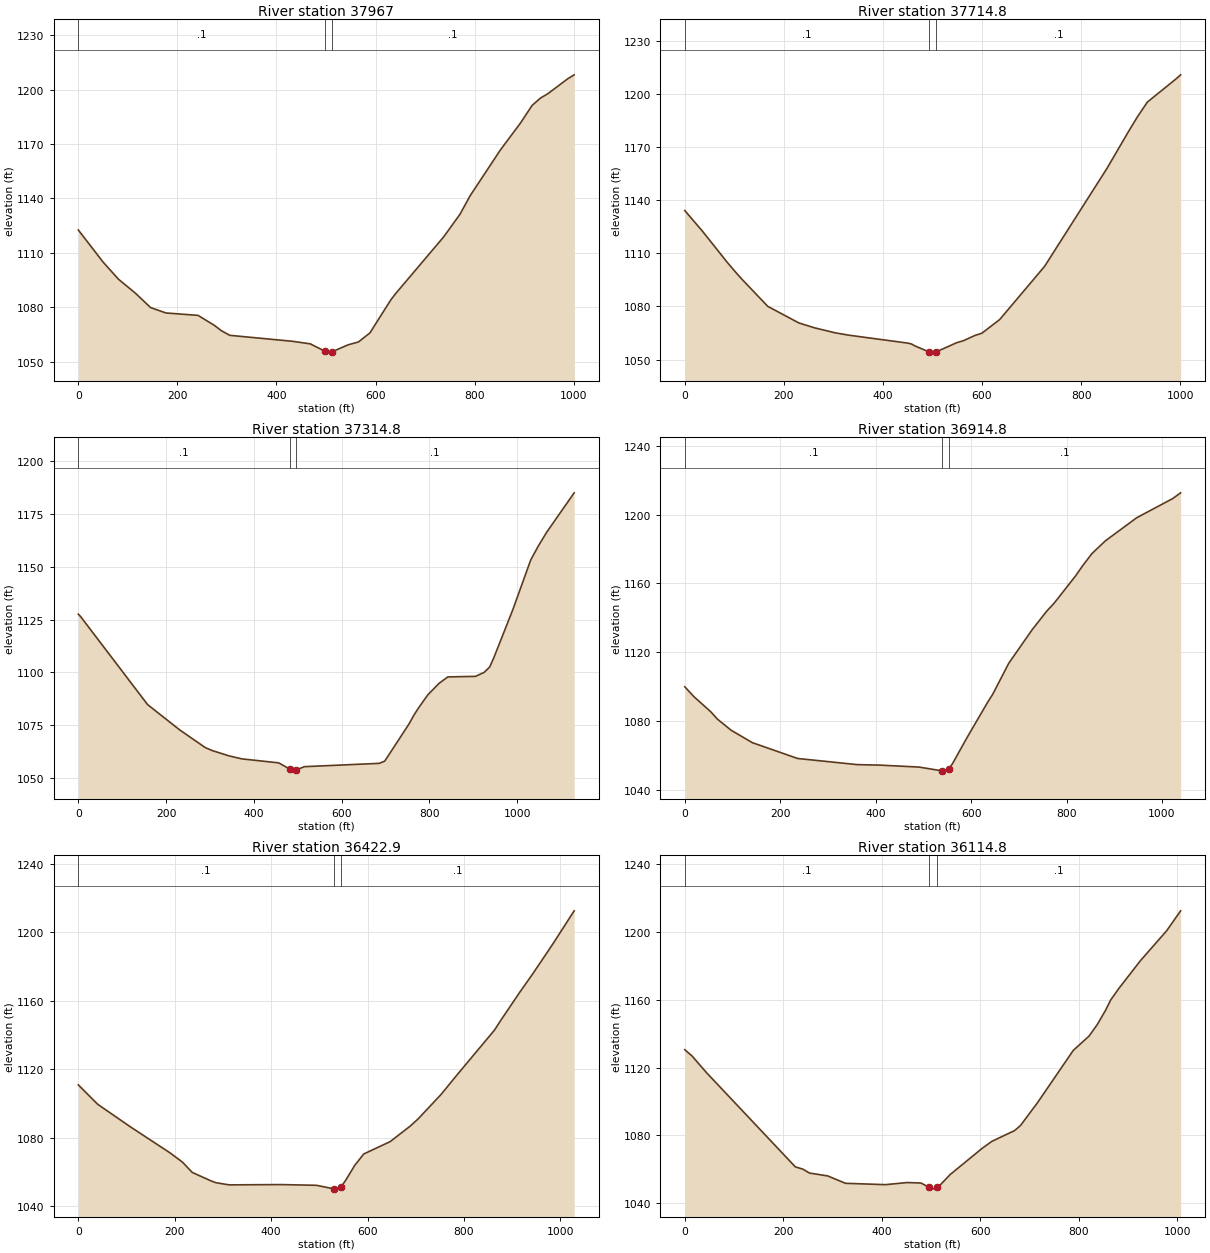
Type RM Length L Ch R = 1 ,37967   ,253.209,252.137,251.064
XS GIS Cut Line= 3
     1666426.598      287350.407     1666489.718      286853.903
     1666552.837      286357.399
#Sta/Elev= 30
       0 1122.56    50.2 1104.82      81 1095.44     115  1087.8   145.9  1079.8
   176.9 1076.83   241.7  1075.5   274.7 1069.99   288.4 1067.12   305.9  1064.5
   433.1 1061.19   468.4 1059.79   497.6 1055.76   505.6 1054.69   512.6 1055.48
   544.2 1059.22   565.7 1060.87   588.7 1065.85   630.6 1083.92   640.2 1087.37
   737.4 1118.71   770.3 1131.15     791 1141.45   851.9 1166.62   892.8 1181.59
   916.1 1191.23   933.3 1195.34   947.8 1197.68   988.4 1205.99    1001  1208.1
#Mann= 3 , 0 , 0
       0      .1       0   497.6    .045       0   512.6      .1       0
Bank Sta=497.6,512.6
XS Rating Curve= 0 ,0
Exp/Cntr=0.3,0.1

Type RM Length L Ch R = 1 ,37714.8 ,402.7,400,392.357
XS GIS Cut Line= 3
     1666701.579      287374.064      1666740.98      286875.117
     1666780.381       286376.17
#Sta/Elev= 30
       0 1134.11    35.6 1122.49    85.7 1104.89   101.2 1099.78   114.5  1095.6
   167.6 1080.01   230.3 1070.66   261.9 1067.91   302.7 1065.14     330  1063.8
   450.5 1059.26   457.7 1058.78   464.3 1057.72     493 1054.34   497.9 1053.76
   502.4 1053.62     508 1054.38   548.9 1059.51   561.9 1060.57   585.6 1063.58
   599.7 1064.86   635.8  1072.6   725.5 1102.32     728 1103.32   852.6 1158.07
   895.4 1178.57   913.4 1186.87   933.8 1195.36     991 1208.29    1001 1210.76
#Mann= 3 , 0 , 0
       0      .1       0     493    .045       0     508      .1       0
Bank Sta=493,508
XS Rating Curve= 0 ,0
Exp/Cntr=0.3,0.1

Type RM Length L Ch R = 1 ,37314.8 ,408.87,400,401.687
XS GIS Cut Line= 3
     1667160.281      287387.033     1667140.169      286898.552
     1666977.042       286278.84
#Sta/Elev= 30
       0 1127.52       5 1126.45   157.8 1084.72   230.8 1072.76   289.5 1064.31
   305.9 1062.89   343.9  1060.4   372.8 1059.01   456.6 1057.12   481.4 1054.24
   490.5 1053.21   496.4 1053.78   515.1 1055.32   685.4 1056.89   698.1 1057.94
   753.6  1075.6   764.3 1079.62   775.9 1083.36   796.1 1089.29     822  1094.8
   841.8 1097.82   904.8 1098.08   924.5 1099.96   937.3 1102.52   946.7 1106.93
   989.7 1129.52  1030.7 1153.17    1048 1159.79  1067.1 1166.33  1129.7 1184.99
#Mann= 3 , 0 , 0
       0      .1       0   481.4    .045       0   496.4      .1       0
Bank Sta=481.4,496.4
XS Rating Curve= 0 ,0
Exp/Cntr=0.3,0.1

Type RM Length L Ch R = 1 ,36914.8 ,476.497,491.968,503.806
XS GIS Cut Line= 3
     1667642.894      287177.472     1667416.522      286679.834
     1667327.198      286195.658
#Sta/Elev= 30
       0  1099.8    18.9  1094.1    54.4 1085.27    68.3    1081      97 1074.53
   141.4  1067.3   236.4 1058.08   361.6  1054.5   409.7  1054.2   490.8 1053.08
   539.2 1050.88   542.9 1050.72   549.8 1051.12   554.2 1052.22   561.1 1055.11
   591.4 1070.19   634.4 1090.67   645.4 1095.48   678.9 1113.46   728.2 1133.09
   758.9 1143.92   772.6 1147.99   780.8  1150.8   818.9 1164.29   833.8 1170.22
   853.1 1177.25   881.3 1184.68     947 1198.13  1022.5  1209.3  1039.1 1212.64
#Mann= 3 , 0 , 0
       0      .1       0   539.2    .045       0   554.2      .1       0
Bank Sta=539.2,554.2
XS Rating Curve= 0 ,0
Exp/Cntr=0.3,0.1

Type RM Length L Ch R = 1 ,36422.9 ,311.563,308.032,301.081
XS GIS Cut Line= 3
      1667743.83      287185.158     1667879.534      286661.077
     1668050.545      286204.676
#Sta/Elev= 30
       0  1110.8    40.1 1099.47     108 1086.26   190.3 1071.02     216 1065.62
   236.4 1059.58   275.7 1054.59   285.4 1053.57     313  1052.3   420.7 1052.47
   493.9 1052.05   529.8 1050.01   533.7 1049.81     543 1050.71   544.8 1051.09
   545.6 1051.26   555.7 1055.42   573.3 1063.61   592.1 1070.36   647.1 1077.62
   688.8 1086.72   705.1 1090.92   752.3  1105.1   786.2 1116.78   863.4 1142.81
   876.3 1148.46   916.2  1165.1   943.6 1176.07   984.2 1193.08  1028.8 1212.63
#Mann= 3 , 0 , 0
       0      .1       0   529.8    .045       0   544.8      .1       0
Bank Sta=529.8,544.8
XS Rating Curve= 0 ,0
Exp/Cntr=0.3,0.1

Type RM Length L Ch R = 1 ,36114.8 ,314.967,321.739,319.578
XS GIS Cut Line= 3
     1668126.215      287244.116     1668173.011      286742.327
     1668188.227       286239.22
#Sta/Elev= 30
       0 1130.54    14.8 1126.82    44.2 1116.95   224.6  1061.3   239.9 1059.96
   253.3 1057.65   290.2 1055.97   326.5  1051.6   407.6  1050.8   451.9 1052.05
   479.8 1051.77   496.5 1049.23   503.7 1048.16   511.5 1049.15   515.5 1049.61
   539.3 1056.83   603.9 1072.21   623.7 1076.37     670 1082.76   681.8 1085.68
   717.1 1099.47   789.2 1130.12   821.2 1138.57   837.9 1145.36   854.9 1153.88
   865.2 1159.91   881.7 1166.68   925.8 1183.21   978.8 1200.77  1007.3  1212.6
#Mann= 3 , 0 , 0
       0      .1       0   496.5    .045       0   511.5      .1       0
Bank Sta=496.5,511.5
XS Rating Curve= 0 ,0
Exp/Cntr=0.3,0.1

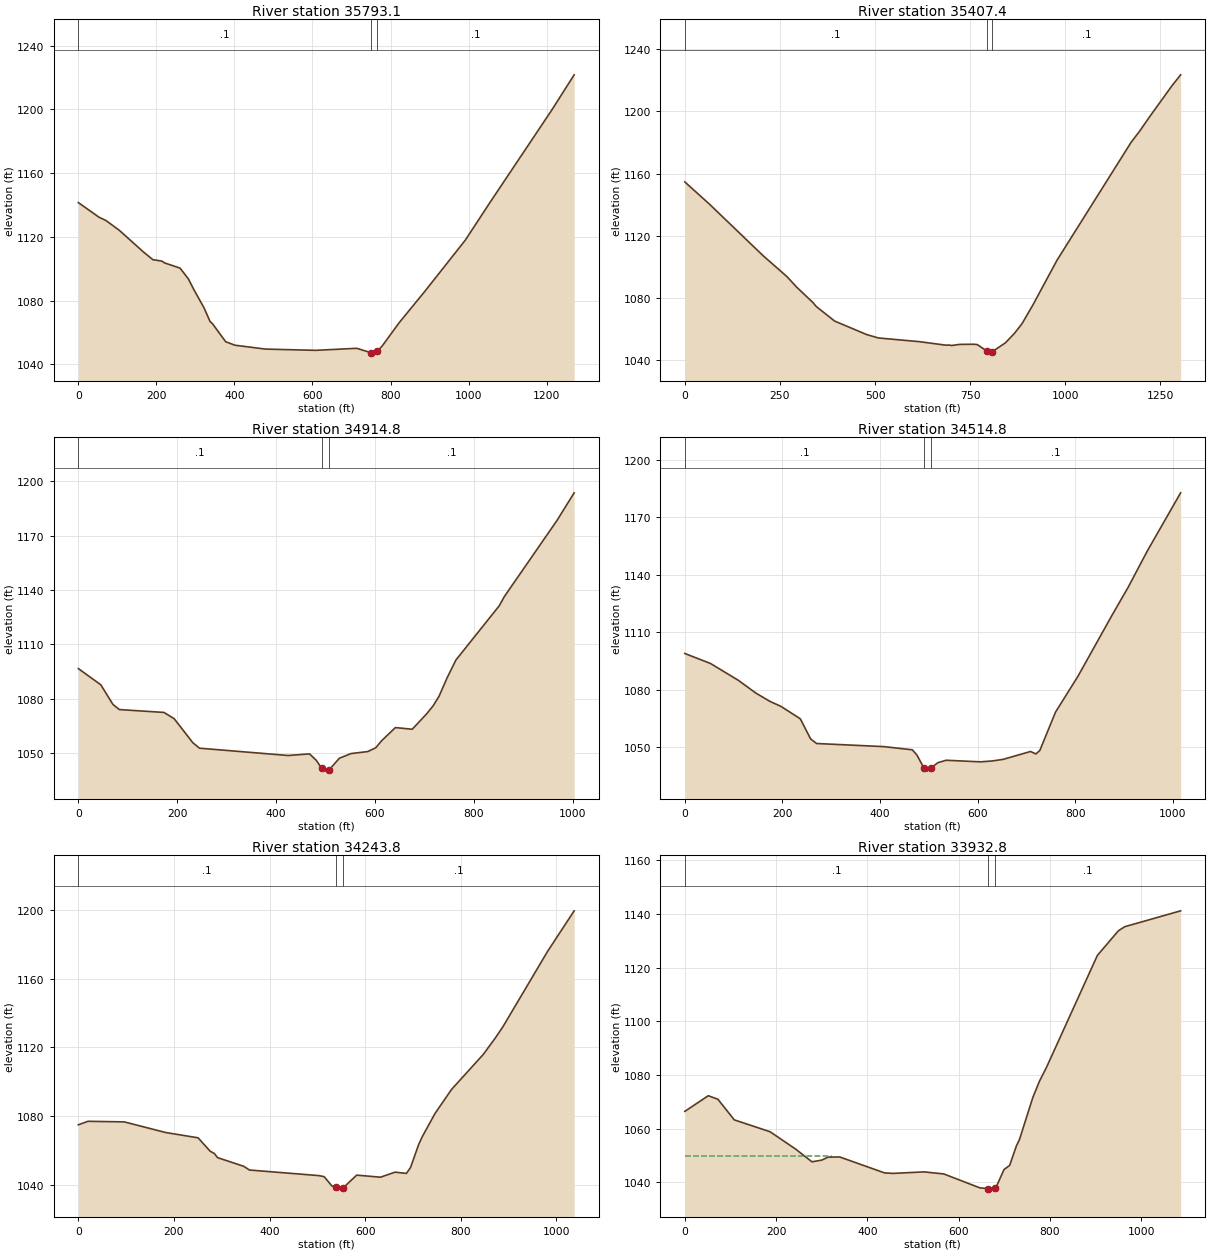
Type RM Length L Ch R = 1 ,35793.1 ,403.792,385.663,377.513
XS GIS Cut Line= 3
     1668196.041      287502.962     1668465.836      286795.702
     1668440.281      286282.777
#Sta/Elev= 30
       0 1141.51    53.2 1132.31    70.6 1130.27   104.7 1124.18   166.6 1110.55
   190.9 1105.67   213.9 1104.78   220.9 1103.63   260.5 1100.37   281.7 1093.72
   296.1 1086.84   322.1 1075.41   337.7 1066.77   343.6 1065.49   377.6 1054.12
   401.3 1051.93   479.6  1049.5   608.2 1048.71   713.2 1049.99   750.6 1047.19
   753.2 1046.96   765.6 1048.57   768.5 1048.77   778.6 1051.43   821.7 1065.95
   887.2 1085.55   991.7 1117.96  1053.5  1141.1  1214.1    1200  1270.5 1221.76
#Mann= 3 , 0 , 0
       0      .1       0   750.6    .045       0   765.6      .1       0
Bank Sta=750.6,765.6
XS Rating Curve= 0 ,0
Exp/Cntr=0.3,0.1

Type RM Length L Ch R = 1 ,35407.4 ,491.031,492.598,495.924
XS GIS Cut Line= 3
     1669119.538      287444.789     1668832.884       286696.26
     1668648.653      286229.988
#Sta/Elev= 30
       0  1154.6    64.8 1140.24   205.2 1107.15   268.9 1093.43   294.2 1086.69
   337.1 1076.74   345.1 1074.33   393.8 1064.87   478.2 1056.15   508.8 1053.98
   615.6 1051.62   685.7 1049.35   695.7 1049.42     701  1049.1   721.7 1049.83
   759.7 1049.94   768.7  1049.7   793.2 1045.65   802.1 1044.21   808.2 1045.21
   842.3 1050.81   866.3 1056.95   886.2 1063.23   914.5 1075.17   978.3 1104.19
    1173 1180.19  1194.3 1186.99    1224 1197.46  1280.3 1216.62  1302.9 1223.61
#Mann= 3 , 0 , 0
       0      .1       0   793.2    .045       0   808.2      .1       0
Bank Sta=793.2,808.2
XS Rating Curve= 0 ,0
Exp/Cntr=0.3,0.1

Type RM Length L Ch R = 1 ,34914.8 ,404.175,400,391.47
XS GIS Cut Line= 3
     1669424.697      286981.231     1669278.018      286503.148
     1669163.323      286013.511
#Sta/Elev= 30
       0 1096.71    45.5 1087.76      70 1076.94      83  1074.1   173.2 1072.52
   193.9 1069.06   231.5 1055.85   245.2  1052.8   424.6 1048.77   467.7 1049.66
   481.1 1046.19   492.6  1041.6     498 1040.15   507.6 1040.92     528 1047.25
   551.4 1049.82   585.6 1050.95   601.8 1053.06     613 1056.76   641.3 1064.16
   675.4 1063.25   704.4 1071.68   717.5 1076.07   729.7 1081.45   746.3 1091.79
   763.8 1101.42   851.6 1131.39   861.8 1136.42   968.2 1178.36    1003 1193.63
#Mann= 3 , 0 , 0
       0      .1       0   492.6    .045       0   507.6      .1       0
Bank Sta=492.6,507.6
XS Rating Curve= 0 ,0
Exp/Cntr=0.3,0.1

Type RM Length L Ch R = 1 ,34514.8 ,269.738,271.022,268.993
XS GIS Cut Line= 3
      1669884.29      286808.044     1669653.391       286367.61
     1669357.069      285941.891
#Sta/Elev= 30
       0 1098.93    52.6 1093.71   109.9 1084.87   145.7 1078.22   174.9 1073.84
     197 1071.29   235.8 1064.94     237 1064.64   257.8 1054.28   270.1 1051.88
   408.2 1050.24   466.2 1048.59   475.5 1045.91   489.8 1039.21   496.8 1037.44
   504.8 1039.09   518.4 1041.84   535.6 1043.12   605.8 1042.29   630.2 1042.76
     652 1043.57   708.5 1047.71   719.3 1046.42   727.5 1048.23   759.7  1068.3
   805.3 1086.87   876.1 1119.21   908.3 1133.45     948  1152.6    1016 1182.89
#Mann= 3 , 0 , 0
       0      .1       0   489.8    .045       0   504.8      .1       0
Bank Sta=489.8,504.8
XS Rating Curve= 0 ,0
Exp/Cntr=0.3,0.1

Type RM Length L Ch R = 1 ,34243.8 ,306.429,310.969,312.53
XS GIS Cut Line= 3
     1670066.819       286659.72     1669832.132      286164.744
     1669508.698      285797.398
#Sta/Elev= 30
       0 1074.86    20.2 1076.89      96 1076.56   182.5 1070.38   250.5 1067.28
   275.8 1059.48   284.5 1058.16   291.3 1055.74   345.6 1050.75   358.1 1048.54
   503.5 1045.28   514.2 1044.67   530.7 1039.21   538.4 1038.53   551.7 1037.42
   553.4 1038.02   582.3 1045.57   632.1 1044.36   662.4 1047.29   686.3 1046.58
   694.9 1049.99   711.9 1063.37   719.9 1068.16     746 1081.38   780.6 1095.41
   847.2 1115.85     872 1125.28   888.1 1131.89   981.4 1175.69  1037.2 1199.39
#Mann= 3 , 0 , 0
       0      .1       0   538.4    .045       0   553.4      .1       0
Bank Sta=538.4,553.4
XS Rating Curve= 0 ,0
Exp/Cntr=0.3,0.1

Type RM Length L Ch R = 1 ,33932.8 ,609.192,618.009,645.409
XS GIS Cut Line= 3
     1670114.586      286576.756     1670012.816      285918.095
     1669765.132      285578.675
#Sta/Elev= 30
       0  1066.4    51.5 1072.24    72.5 1070.93   108.5 1063.23   186.8 1058.82
     243 1052.33   278.7  1047.6   300.3 1048.24   314.1 1049.35   339.4 1049.41
   437.8 1043.47   456.9 1043.28   524.2 1043.85   567.9 1043.07   646.7 1037.89
   664.6 1037.63   673.6 1037.42   679.6 1037.96   682.7 1038.27   699.6 1044.72
     712 1046.26   726.7 1053.51   733.4 1055.86   762.8 1071.59   777.5 1077.71
   793.1 1082.94   904.2 1124.51   950.2  1133.7   964.4 1135.24  1086.7 1141.15
#Mann= 3 , 0 , 0
       0      .1       0   664.6    .045       0   679.6      .1       0
#XS Ineff= 2 , 0
          320.99 1049.67
Permanent Ineff=
       F       F
Bank Sta=664.6,679.6
XS Rating Curve= 0 ,0
Exp/Cntr=0.3,0.1

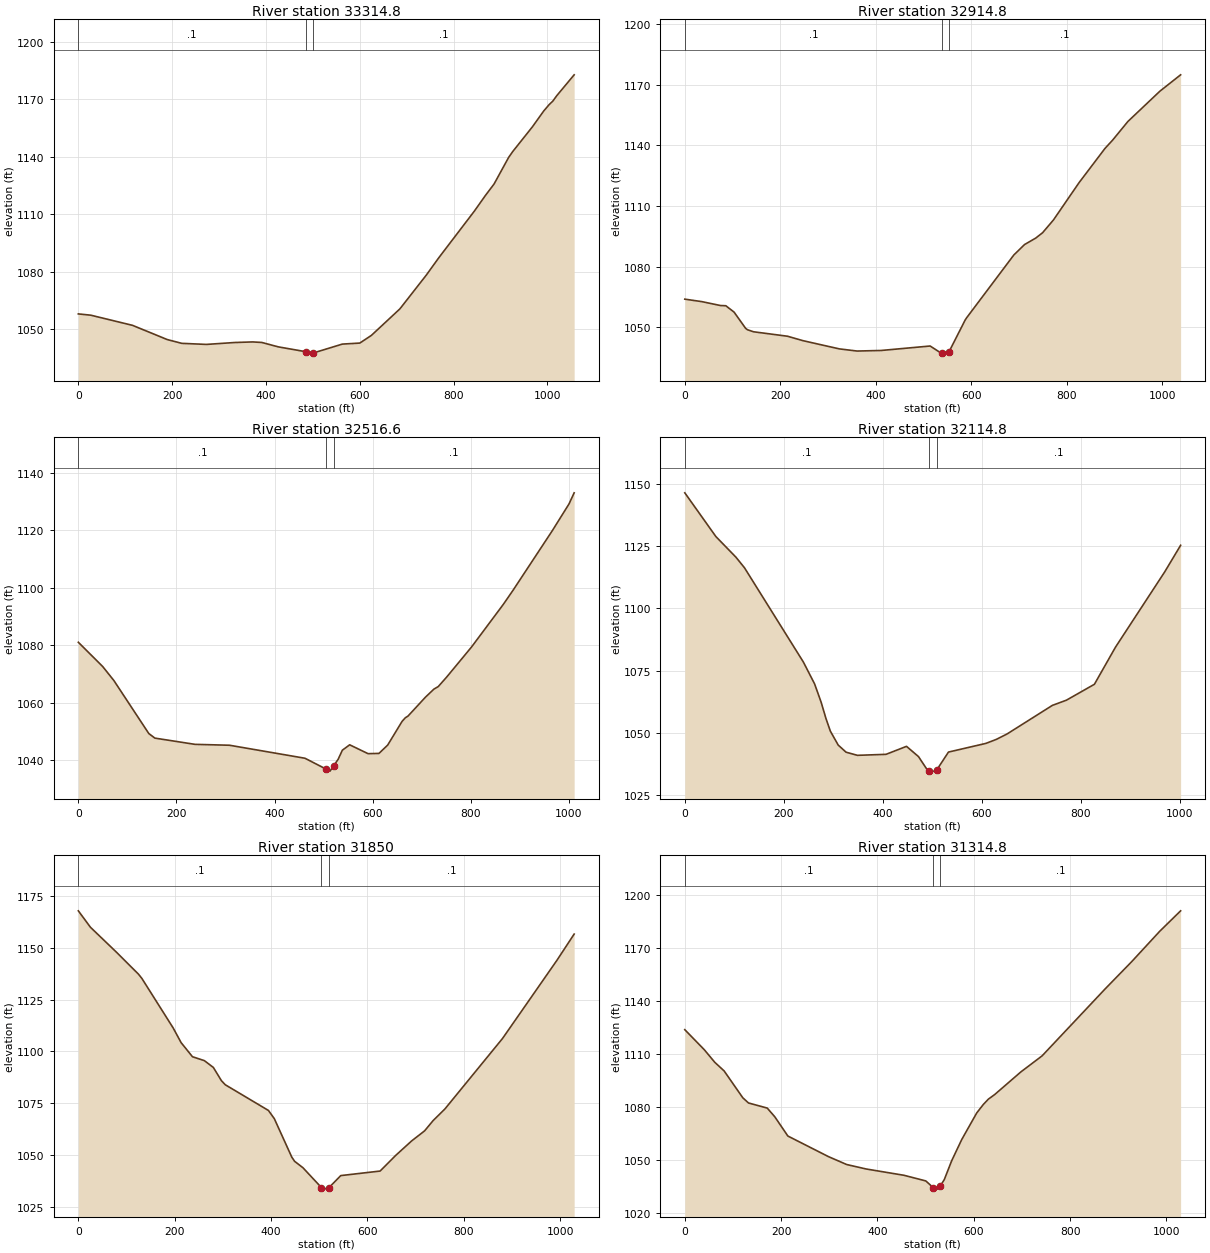
Type RM Length L Ch R = 1 ,33314.8 ,390.945,400,396.099
XS GIS Cut Line= 3
     1670348.444      286476.916     1670426.228      285991.123
     1670732.389      285516.234
#Sta/Elev= 30
       0 1057.94    26.6 1057.27   115.5 1051.97   189.6 1044.54   220.5 1042.57
   273.1 1042.01     333    1043   371.4 1043.31   391.1 1043.03   426.3 1040.73
   484.5 1038.22   499.5 1037.47   499.8 1037.46   562.9 1042.18     600 1042.71
   624.7 1046.71   685.4 1060.54   741.6 1078.14     769 1087.45   844.3 1111.63
   867.3 1119.61   886.2 1125.75   917.4  1139.7   926.4 1142.83     968 1155.63
   992.1 1163.89  1003.8 1167.26  1011.3    1169    1020 1171.92    1057 1182.79
#Mann= 3 , 0 , 0
       0      .1       0   484.5    .045       0   499.5      .1       0
Bank Sta=484.5,499.5
XS Rating Curve= 0 ,0
Exp/Cntr=0.3,0.1

Type RM Length L Ch R = 1 ,32914.8 ,392.739,398.195,407.606
XS GIS Cut Line= 3
     1670527.744      286525.228     1670815.748      286062.097
     1671008.545      285608.815
#Sta/Elev= 30
       0 1063.96    35.4 1062.75    74.7 1060.81    85.9  1060.7   103.2 1057.54
   127.2 1049.57     131 1048.86   143.7 1047.83     215 1045.62   247.3 1043.43
   323.5 1039.36   360.6 1038.29   410.9 1038.57   513.6 1040.78   536.7 1037.26
   537.9 1037.29   552.9  1037.8     587 1053.66     590 1054.74   688.8  1085.8
   711.3 1090.98   734.8 1094.19     749 1096.82   771.7 1103.11   825.1  1121.5
   879.6 1138.51   895.7 1142.65   927.7 1151.88   994.6 1166.84    1038 1174.94
#Mann= 3 , 0 , 0
       0      .1       0   537.9    .045       0   552.9      .1       0
Bank Sta=537.9,552.9
XS Rating Curve= 0 ,0
Exp/Cntr=0.3,0.1

Type RM Length L Ch R = 1 ,32516.6 ,403.38,401.805,400.124
XS GIS Cut Line= 3
      1670674.34      286709.279     1671040.458      286351.477
     1671404.466      286010.116
#Sta/Elev= 30
       0 1080.97    49.7 1072.53    72.5 1067.66   143.7 1049.23   156.1 1047.64
   237.9 1045.47   308.3 1045.16   462.1 1040.64   505.4 1036.85   513.2 1036.16
   520.4 1037.97   529.7 1040.25   538.4 1043.45   553.3 1045.31   590.8 1042.23
     613 1042.32   630.8 1045.22   660.2 1053.48   666.8 1054.72   672.3 1055.32
   707.7 1061.86     725 1064.67   733.8 1065.55   750.7  1068.8   801.5 1079.27
   866.4 1094.11   886.5 1099.08   966.7 1119.84  1000.5 1129.07    1011 1132.94
#Mann= 3 , 0 , 0
       0      .1       0   505.4    .045       0   520.4      .1       0
Bank Sta=505.4,520.4
XS Rating Curve= 0 ,0
Exp/Cntr=0.3,0.1

Type RM Length L Ch R = 1 ,32114.8 ,261.303,264.867,268.078
XS GIS Cut Line= 3
     1670972.196      287009.888     1671305.641      286634.969
     1671643.851      286266.464
#Sta/Elev= 30
       0 1146.44    62.8 1128.86   103.4 1120.55   120.7 1116.28   239.6 1078.41
   262.3 1069.61   275.6 1062.21   285.2 1055.73   294.1 1050.65     310 1045.02
   325.9 1042.16   348.8  1040.9   406.6  1041.3     448 1044.51   472.2  1040.4
   490.7 1034.84   494.2 1034.74   500.7 1034.55   507.5 1034.56   509.2 1035.05
   532.8 1042.21   608.4  1045.7   629.6 1047.32   651.3  1049.5   742.8 1060.99
   771.1 1063.07   827.7 1069.47   870.3 1084.39   969.7 1114.64  1001.9 1125.35
#Mann= 3 , 0 , 0
       0      .1       0   494.2    .045       0   509.2      .1       0
Bank Sta=494.2,509.2
XS Rating Curve= 0 ,0
Exp/Cntr=0.3,0.1

Type RM Length L Ch R = 1 ,31850   ,527.942,535.133,542.736
XS GIS Cut Line= 3
     1671091.079      287150.896     1671514.985      286803.563
      1671885.06      286496.057
#Sta/Elev= 30
       0 1167.87    25.1 1159.95    78.8 1147.98   124.8 1137.31   131.9 1135.25
   196.9 1111.33   213.3 1104.28   236.9 1097.46   261.6 1095.57   280.2  1092.3
   297.1 1085.88   305.1 1083.92   394.6 1071.53   406.8 1067.58   443.1 1048.99
     449 1046.97   466.1 1043.92   504.6 1034.32   516.5 1033.56   519.6 1034.12
   544.7 1040.09   626.4 1042.28   658.9 1049.86   691.9 1056.83   718.8 1061.69
   736.3  1066.6   760.9 1072.24   880.5 1106.26   993.2 1143.91  1029.2 1156.65
#Mann= 3 , 0 , 0
       0      .1       0   504.6    .045       0   519.6      .1       0
Bank Sta=504.6,519.6
XS Rating Curve= 0 ,0
Exp/Cntr=0.3,0.1

Type RM Length L Ch R = 1 ,31314.8 ,408.022,400,389.03
XS GIS Cut Line= 3
      1671308.67      287357.121     1671798.454      287173.602
     1672275.635      287003.877
#Sta/Elev= 30
       0 1123.99    40.4 1112.67    62.2 1105.53    81.7 1100.62   120.5 1085.41
   132.2 1082.49   171.2 1079.59   186.9 1074.65     214 1063.77   298.1 1052.13
     336 1047.64   376.4 1045.11     455 1041.54   500.4 1038.35   515.5 1034.62
   526.2  1033.7   530.5 1035.49   538.8 1039.09   554.1 1049.75   575.1 1061.82
   606.2 1076.86   619.8 1081.62   630.4 1084.67   643.4 1087.25   697.7 1100.05
   741.9 1109.17   872.9 1147.11   927.8 1162.48   986.2 1179.73  1029.5 1191.29
#Mann= 3 , 0 , 0
       0      .1       0   515.5    .045       0   530.5      .1       0
Bank Sta=515.5,530.5
XS Rating Curve= 0 ,0
Exp/Cntr=0.3,0.1