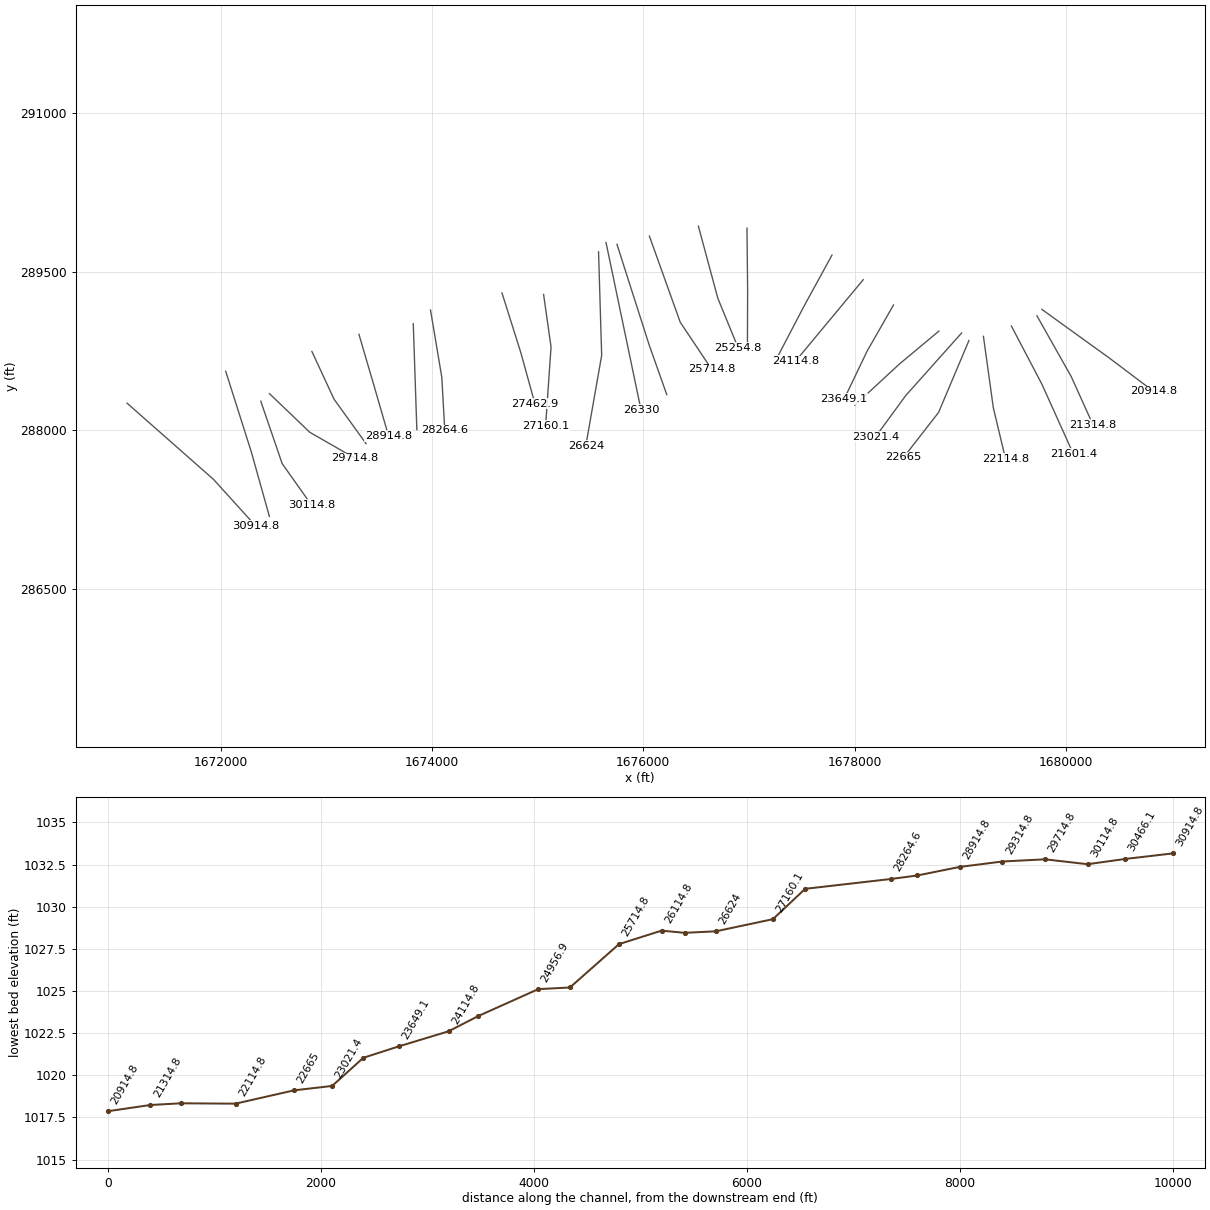
HEC-RAS study SalemFk.prj: SalemFk

--- SalemFk.g01 (geometry) --- (continued)

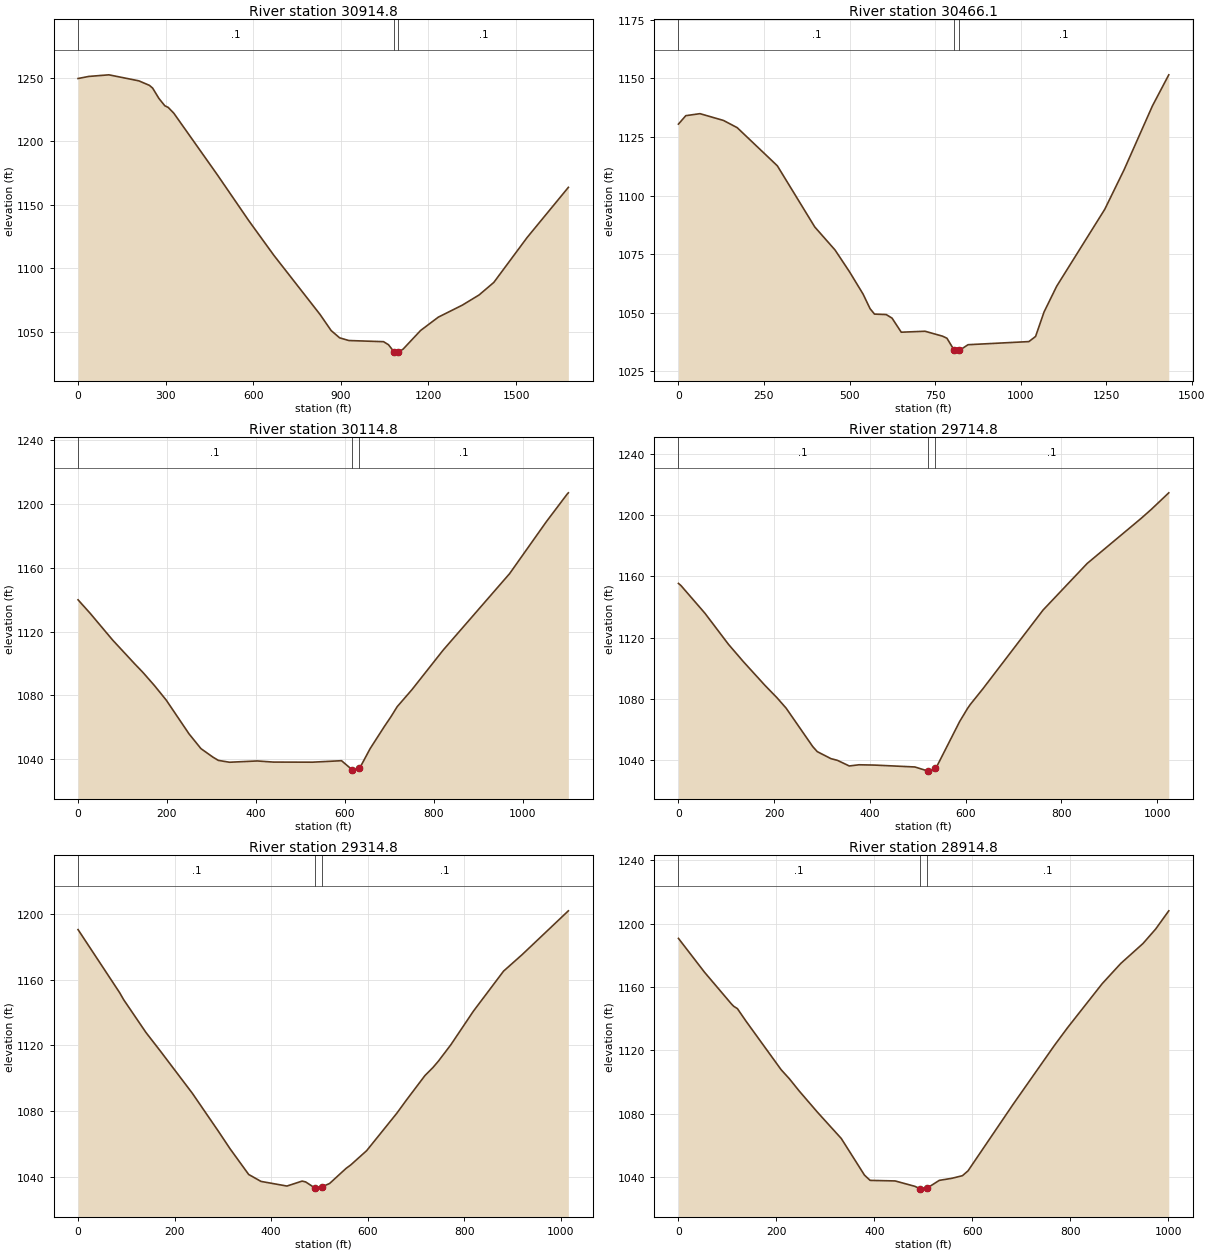
Type RM Length L Ch R = 1 ,30914.8 ,461.42,448.718,438.334
XS GIS Cut Line= 3
     1671115.541      288257.405      1671933.28      287536.952
     1672328.927      287100.462
#Sta/Elev= 30
       0 1249.49    36.6 1251.13   105.6  1252.4   208.1 1247.66   244.3 1244.11
   255.3 1241.97     277 1233.77     297 1228.06     309 1226.68     328 1222.14
   477.3 1173.54   585.2 1137.32   670.5 1110.22     829 1063.52   866.6 1050.96
   895.6 1045.22   927.3 1043.08  1046.1 1042.18  1062.9 1039.79  1082.3  1034.1
  1091.5 1033.16  1097.3 1034.04  1113.3 1036.36    1173    1051  1233.4 1061.46
  1316.5 1071.05  1373.2 1078.97  1423.8 1088.89  1538.1 1124.35    1679 1163.75
#Mann= 3 , 0 , 0
       0      .1       0  1082.3    .045       0  1097.3      .1       0
Bank Sta=1082.3,1097.3
XS Rating Curve= 0 ,0
Exp/Cntr=0.3,0.1

Type RM Length L Ch R = 1 ,30466.1 ,350.42,351.282,359.005
XS GIS Cut Line= 3
     1672048.661      288559.048     1672290.364      287798.675
     1672461.887       287187.03
#Sta/Elev= 30
       0 1130.49    21.4 1134.08    62.9 1134.94   131.7 1132.04   171.7 1128.97
     289 1112.71   398.5 1086.61   457.7  1076.8   499.9 1067.53   539.6 1058.01
     560  1051.8     573 1049.47   607.3 1049.27   624.3 1047.75   651.2 1041.75
   720.7 1042.16   772.3 1040.04   784.8 1039.16   805.7 1034.14   812.5 1032.83
   820.7 1033.98   846.5 1036.42  1024.3 1037.75  1043.8 1039.94  1068.5 1050.36
  1105.5 1061.36    1246 1094.16  1302.8 1111.11  1385.3 1138.25  1433.1  1151.5
#Mann= 3 , 0 , 0
       0      .1       0   805.7    .045       0   820.7      .1       0
Bank Sta=805.7,820.7
XS Rating Curve= 0 ,0
Exp/Cntr=0.3,0.1

Type RM Length L Ch R = 1 ,30114.8 ,389.19,400,409.749
XS GIS Cut Line= 3
     1672380.518      288276.403     1672582.828      287686.077
     1672859.891      287295.707
#Sta/Elev= 30
       0 1139.93      27 1131.54    77.6 1114.76   126.4 1100.08   146.2 1094.32
   171.6 1086.23   198.3 1077.06   249.6 1055.87   276.4 1046.63   303.5 1041.26
   315.6 1039.25   340.7 1038.09   403.1  1038.9   439.2 1038.19   527.3 1038.13
   592.5 1039.06   616.5 1033.38   620.7 1032.52   631.5  1034.6   635.4 1035.43
   656.9 1046.64   689.1 1060.61   703.6 1066.58   717.7 1072.92   750.9  1083.6
     821 1108.36   970.5 1156.33    1053 1188.84  1100.5 1206.39  1102.7 1207.01
#Mann= 3 , 0 , 0
       0      .1       0   616.5    .045       0   631.5      .1       0
Bank Sta=616.5,631.5
XS Rating Curve= 0 ,0
Exp/Cntr=0.3,0.1

Type RM Length L Ch R = 1 ,29714.8 ,408.32,400,390.435
XS GIS Cut Line= 3
     1672462.447      288348.121      1672844.42      287982.337
     1673274.273       287735.88
#Sta/Elev= 30
       0 1155.29     5.3 1153.88    55.4 1135.81   104.4 1115.59     136 1104.12
   181.5 1088.51   206.1 1080.62     225 1073.88   280.7 1048.77   290.1 1045.51
   318.7 1040.94   332.1 1039.85   356.9 1036.17   377.2 1036.95   409.9 1036.75
     494 1035.52   521.4 1032.84   521.7 1032.81   533.8 1033.48   536.4 1034.53
   539.9 1035.94   587.5 1065.18   603.7 1073.59   609.9 1076.38     636 1086.52
   761.8 1137.94   853.9 1168.32   966.6 1197.73   987.8 1203.59  1024.4 1214.42
#Mann= 3 , 0 , 0
       0      .1       0   521.4    .045       0   536.4      .1       0
Bank Sta=521.4,536.4
XS Rating Curve= 0 ,0
Exp/Cntr=0.3,0.1

Type RM Length L Ch R = 1 ,29314.8 ,403.35,400,392.243
XS GIS Cut Line= 3
     1672864.454      288746.386     1673073.765      288295.187
     1673376.847      287874.919
#Sta/Elev= 30
       0 1190.33    86.1 1152.04    94.4 1147.79   140.6 1127.86   170.1  1116.7
   236.7 1090.91   290.1 1068.07     315 1057.13   353.4 1041.58     379 1037.36
   432.6 1034.55     464 1037.55   471.5 1037.04   489.9 1033.49   494.1 1032.68
   504.9 1034.06   520.9 1036.09   554.9 1045.23   564.8 1047.38   597.8 1056.07
   660.1 1078.75   679.8 1086.67   718.3 1101.62   735.3 1106.64   746.5  1110.5
   772.1 1120.39   818.8 1140.79   881.3 1165.12   919.9 1175.18  1015.5 1201.75
#Mann= 3 , 0 , 0
       0      .1       0   489.9    .045       0   504.9      .1       0
Bank Sta=489.9,504.9
XS Rating Curve= 0 ,0
Exp/Cntr=0.3,0.1

Type RM Length L Ch R = 1 ,28914.8 ,405.67,400,394.399
XS GIS Cut Line= 3
     1673309.285      288908.728     1673450.275       288428.44
     1673589.744      287947.819
#Sta/Elev= 30
       0 1190.68    53.1 1169.35     108 1149.34   112.8 1147.81   120.4 1146.31
   137.8 1138.46   209.6 1107.77   226.7 1101.94   245.9 1094.55   282.9 1081.23
   332.4 1064.33   379.8 1041.19   391.3 1037.88   442.3 1037.53   482.5 1034.14
   493.1 1032.63     495 1032.36   508.1  1033.1   532.5 1037.89   558.2 1039.19
   579.8 1040.85   591.1 1043.88   683.7 1086.13   767.7 1123.17   794.4 1134.31
   865.2 1162.13     903 1174.85   948.3 1187.42   974.3 1196.61    1001 1208.08
#Mann= 3 , 0 , 0
       0      .1       0   493.1    .045       0   508.1      .1       0
Bank Sta=493.1,508.1
XS Rating Curve= 0 ,0
Exp/Cntr=0.3,0.1

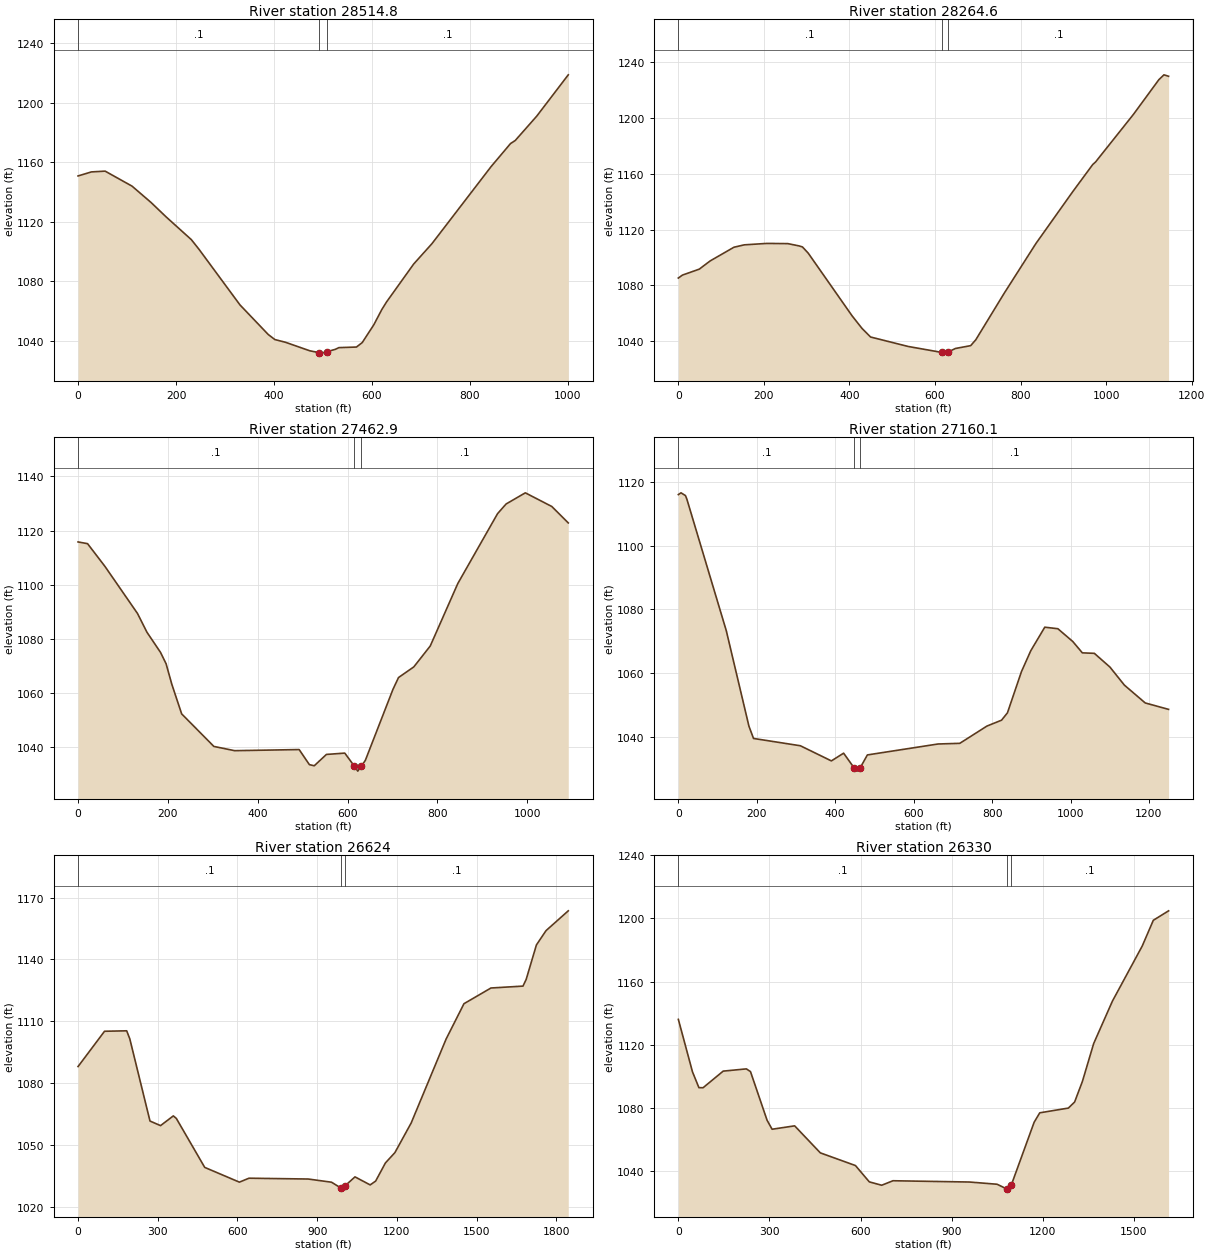
Type RM Length L Ch R = 1 ,28514.8 ,247.255,250.247,253.189
XS GIS Cut Line= 3
     1673823.549      289008.303     1673840.386      288508.086
     1673857.222       288007.87
#Sta/Elev= 30
       0 1150.84    27.3 1153.55    55.3 1154.07   110.3 1143.98   148.8  1133.1
   180.2 1123.23   231.5 1108.01   247.2 1101.48   330.6 1064.25   388.4 1044.34
   401.9 1040.96   423.6 1039.13   473.2 1033.42     493 1032.12   496.9 1031.85
     508 1032.78   525.5 1034.42   532.6 1035.54   568.5 1035.94   580.3 1038.95
   603.8 1050.82   620.3 1061.14   629.7 1066.11   685.3 1091.68   722.6 1105.35
   843.5 1157.16   883.2 1172.63   892.6  1174.6   936.5 1190.96    1001 1218.75
#Mann= 3 , 0 , 0
       0      .1       0     493    .045       0     508      .1       0
Bank Sta=493,508
XS Rating Curve= 0 ,0
Exp/Cntr=0.3,0.1

Type RM Length L Ch R = 1 ,28264.6 ,799.539,801.715,803.941
XS GIS Cut Line= 3
     1673986.582       289138.44     1674093.569      288501.759
     1674121.471       288002.23
#Sta/Elev= 30
       0 1085.31     9.5 1087.41    48.9 1091.67    74.3 1097.54   129.9 1107.32
     154 1109.03   206.5 1110.05     256 1109.91   282.4 1108.26   290.1 1107.54
   303.6 1103.09   406.2 1058.26   429.2 1049.34   449.3 1043.16   536.9 1036.42
     616 1032.13   623.5 1031.64     631 1032.51   647.6 1034.95   683.3 1036.99
   695.2 1041.15   761.3 1074.26   835.8 1109.99   922.2 1147.19   968.7 1166.47
   975.3  1168.3  1063.9 1202.35  1123.2  1227.1  1135.1 1230.56  1145.9 1229.52
#Mann= 3 , 0 , 0
       0      .1       0     616    .045       0     631      .1       0
Bank Sta=616,631
XS Rating Curve= 0 ,0
Exp/Cntr=0.3,0.1

Type RM Length L Ch R = 1 ,27462.9 ,305.528,302.759,299.99
XS GIS Cut Line= 3
     1674663.015      289299.976     1674840.829      288736.813
     1674974.217       288254.42
#Sta/Elev= 30
       0 1115.79    21.2 1115.14    59.8 1106.76   132.4 1089.32   153.3 1082.42
   183.5 1074.97   195.9 1070.78   208.7 1063.18   230.6 1052.23   302.3 1040.19
   348.6 1038.62   492.1 1039.03   514.9 1033.46   525.7 1033.04   552.8 1037.23
   593.7 1037.72   615.1 1032.87   622.6 1031.06   630.1  1032.8   639.4 1035.03
     701 1061.33   713.3 1065.66   747.3 1069.59   783.9 1077.32   845.2  1100.4
   933.7 1126.24   952.7 1129.81   995.5 1133.94  1054.4 1128.89  1091.1 1122.82
#Mann= 3 , 0 , 0
       0      .1       0   615.1    .045       0   630.1      .1       0
Bank Sta=615.1,630.1
XS Rating Curve= 0 ,0
Exp/Cntr=0.3,0.1

Type RM Length L Ch R = 1 ,27160.1 ,539.945,536.078,529.3
XS GIS Cut Line= 3
      1675056.63      289285.698     1675127.107      288789.516
     1675075.583      288042.371
#Sta/Elev= 30
       0 1116.01     6.8 1116.56    18.2 1115.68    21.8 1114.54   122.3 1073.28
     180 1043.35   191.7 1039.51   311.1 1037.22   390.2 1032.47   421.4 1034.89
   448.5 1030.23     458 1029.26   463.5 1030.25     482 1034.34   662.2 1037.77
   717.7 1037.98     787  1043.4   824.2 1045.24   839.2 1047.55   874.9 1060.47
   898.7 1067.03   934.4 1074.41   967.8 1073.93  1005.8 1069.92  1030.2 1066.36
  1060.8 1066.21  1100.5 1061.91  1137.3 1056.25  1190.5 1050.65  1250.1 1048.63
#Mann= 3 , 0 , 0
       0      .1       0   448.5    .045       0   463.5      .1       0
Bank Sta=448.5,463.5
XS Rating Curve= 0 ,0
Exp/Cntr=0.3,0.1

Type RM Length L Ch R = 1 ,26624   ,289.262,294.05,301.75
XS GIS Cut Line= 3
     1675576.705      289688.673     1675606.269       288710.22
     1675456.474      287856.937
#Sta/Elev= 30
       0 1088.01    99.7 1105.13   183.1 1105.35   194.8 1101.44   270.8 1061.57
   310.5 1059.35   358.6 1064.06   369.9 1062.85   476.8 1039.08   607.3 1031.93
   643.3 1033.84   866.4 1033.44   953.9  1031.9   988.8 1029.15   995.1 1028.54
  1003.8 1030.02  1042.4 1034.48  1099.6 1030.59  1120.2 1032.45  1157.1 1041.28
  1192.6 1046.25  1253.8 1060.61  1385.4 1101.36  1452.6  1118.5  1554.2 1126.12
  1674.7 1127.04  1686.8 1130.31  1725.3 1147.02  1761.4 1153.94  1845.2 1163.56
#Mann= 3 , 0 , 0
       0      .1       0   988.8    .045       0  1003.8      .1       0
Bank Sta=988.8,1003.8
XS Rating Curve= 0 ,0
Exp/Cntr=0.3,0.1

Type RM Length L Ch R = 1 ,26330   ,212.065,215.152,218.929
XS GIS Cut Line= 3
     1675647.377      289777.013     1675871.229      288707.182
     1675978.021      288196.986
#Sta/Elev= 30
       0 1136.01    46.5 1102.79    67.7 1092.75    81.4  1092.7   147.7 1103.23
   223.9 1104.64   237.5 1102.94   292.2 1072.08   308.7  1066.4     383 1068.55
   467.5 1051.43   583.2 1043.39   628.8 1033.05   669.6 1030.91   706.8 1033.76
   958.9 1032.95  1049.7 1031.54  1081.5 1028.56  1082.8 1028.45  1096.5 1031.09
  1171.5 1070.79  1190.1  1076.8  1284.3 1079.81  1304.9 1083.66  1330.5 1096.69
  1367.7 1120.73  1429.4  1147.6  1527.6 1182.52    1564  1198.8  1614.3  1204.8
#Mann= 3 , 0 , 0
       0      .1       0  1081.5    .045       0  1096.5      .1       0
Bank Sta=1081.5,1096.5
XS Rating Curve= 0 ,0
Exp/Cntr=0.3,0.1

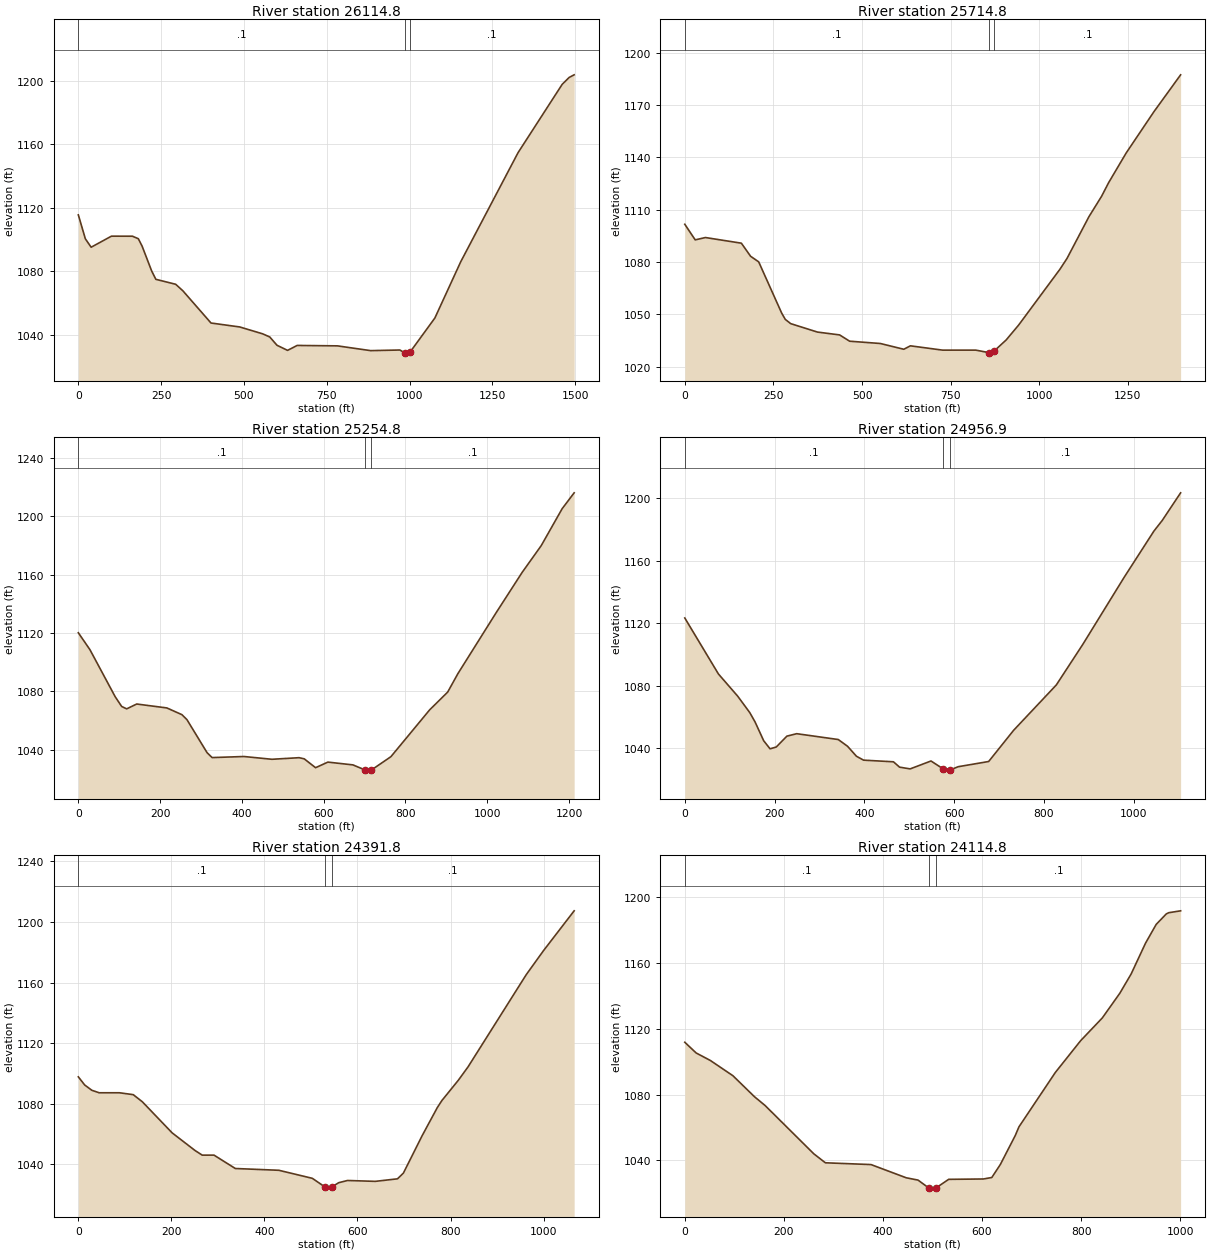
Type RM Length L Ch R = 1 ,26114.8 ,399.158,400,406.48
XS GIS Cut Line= 3
     1675751.104      289759.553     1676054.407      288812.456
     1676222.093      288339.016
#Sta/Elev= 30
       0 1115.57    21.2  1100.5    38.7 1095.21    99.9 1102.17   163.4 1102.14
   181.1 1100.56   192.6 1095.87   221.3 1080.29     234 1075.01   293.9  1071.9
   315.5 1067.81   400.5 1047.52   487.1 1045.05   556.3 1040.73   577.8 1038.75
   599.7 1033.53   631.6 1030.31   660.5 1033.41   782.1 1033.15   882.3 1030.15
   970.7 1030.54   986.2 1028.58     987 1028.63    1002 1029.41  1076.3 1050.68
  1154.3 1086.06  1327.3 1154.68  1460.6  1197.7  1481.6 1202.03  1496.7 1203.68
#Mann= 3 , 0 , 0
       0      .1       0     987    .045       0    1002      .1       0
Bank Sta=987,1002
XS Rating Curve= 0 ,0
Exp/Cntr=0.3,0.1

Type RM Length L Ch R = 1 ,25714.8 ,461.289,460.063,454.914
XS GIS Cut Line= 3
     1676057.819      289837.489     1676349.567      289023.521
     1676646.469      288579.337
#Sta/Elev= 30
       0 1101.63    29.4 1092.69    58.2 1094.03   159.6 1090.79   185.7 1083.28
   208.5 1080.09   273.3 1050.74   283.6 1047.09   298.8 1044.68   374.2 1039.85
   436.8 1038.22   465.1 1034.61   551.6  1033.3   617.8    1030   636.6 1031.96
   727.4 1029.49   820.9  1029.5   857.2 1028.11   866.3 1027.78   872.2 1028.88
   906.9 1035.37     942 1043.89  1058.5 1075.88  1078.3 1082.03  1140.3    1106
  1175.9 1117.66  1195.9 1125.52  1245.5 1142.55  1323.3 1166.06  1398.9 1187.28
#Mann= 3 , 0 , 0
       0      .1       0   857.2    .045       0   872.2      .1       0
Bank Sta=857.2,872.2
XS Rating Curve= 0 ,0
Exp/Cntr=0.3,0.1

Type RM Length L Ch R = 1 ,25254.8 ,304.037,297.878,289.168
XS GIS Cut Line= 3
     1676521.565      289931.734     1676705.356      289250.085
     1676897.515      288781.283
#Sta/Elev= 30
       0 1120.16    28.4 1108.54    90.2 1076.23   105.9 1069.61   118.2 1067.93
   142.8 1071.26   216.5 1068.57   253.4 1063.95   265.7 1060.51   314.9 1037.85
   327.2  1034.5     405 1035.24   473.6 1033.34   539.9 1034.43   552.5 1033.64
   580.2 1027.56   610.3  1031.4   671.5 1029.49   701.9 1025.93     708 1025.21
   716.9 1026.01   764.5 1035.13   859.2 1067.25   903.3 1079.45     928 1091.97
    1022    1134  1085.4 1161.58  1132.1 1179.96  1183.3 1205.31  1212.6 1216.18
#Mann= 3 , 0 , 0
       0      .1       0   701.9    .045       0   716.9      .1       0
Bank Sta=701.9,716.9
XS Rating Curve= 0 ,0
Exp/Cntr=0.3,0.1

Type RM Length L Ch R = 1 ,24956.9 ,576.548,565.055,554.037
XS GIS Cut Line= 3
     1676981.389       289912.51     1676987.519      289316.775
     1676985.542       288808.36
#Sta/Elev= 30
       0 1123.34    74.9 1087.43   117.8 1073.19   144.7 1062.65   156.5 1056.65
   175.8 1044.55   189.9 1039.43   203.6 1040.57   227.4 1047.55   249.2 1049.12
   341.8 1045.38   362.5 1041.03   382.3 1034.64   398.2 1032.15   464.7 1031.09
   478.3 1027.66   501.8 1026.54   548.3 1031.61   575.9 1026.46   581.7 1025.11
   590.9 1025.83   608.6 1027.93   676.7 1031.28   732.4 1051.33   827.3 1080.36
   886.1 1106.28   978.7 1149.55  1044.7 1179.07  1063.2 1185.88  1104.2 1203.62
#Mann= 3 , 0 , 0
       0      .1       0   575.9    .045       0   590.9      .1       0
Bank Sta=575.9,590.9
XS Rating Curve= 0 ,0
Exp/Cntr=0.3,0.1

Type RM Length L Ch R = 1 ,24391.8 ,281.338,277.004,272.339
XS GIS Cut Line= 3
     1677785.713      289657.788     1677524.302      289180.998
     1677282.338       288718.54
#Sta/Elev= 30
       0  1097.7    13.6 1092.34      29 1088.83    44.8 1087.17    88.5 1087.17
     118 1085.93   137.5 1081.25   201.6 1060.69     251 1048.99   266.3 1045.97
   291.6 1045.98   337.4 1037.14     431 1035.96   502.9 1030.65   530.8  1024.8
   537.3 1023.51   545.8 1025.15   559.6 1027.75   578.6 1029.22   638.2 1028.64
     686 1030.32   698.7 1034.12     739 1058.83   771.6  1077.4   781.5 1082.07
   816.8 1095.46   837.6 1104.27   962.7  1165.2   999.7 1181.03  1065.7 1207.39
#Mann= 3 , 0 , 0
       0      .1       0   530.8    .045       0   545.8      .1       0
Bank Sta=530.8,545.8
XS Rating Curve= 0 ,0
Exp/Cntr=0.3,0.1

Type RM Length L Ch R = 1 ,24114.8 ,461.791,465.725,471.194
XS GIS Cut Line= 3
     1678081.321        289425.2     1677761.258      289040.415
     1677441.194       288655.63
#Sta/Elev= 30
       0 1111.79      23 1105.27    51.5 1100.75    97.2 1091.46   140.6 1078.74
   162.1 1073.39   260.4 1044.07   283.8  1038.6   375.9 1037.52     447  1029.5
   470.9 1028.09     493 1023.23   496.4 1022.61     508  1023.5   532.7 1028.55
   602.8 1028.77   619.8 1029.67   637.1  1037.6   667.2 1055.18   674.6 1060.42
     748 1093.42   799.1 1112.73   842.8 1126.53   878.2 1141.52   901.1 1153.25
   930.1 1171.93   951.7 1183.37   972.1 1189.73     977 1190.46    1001  1191.6
#Mann= 3 , 0 , 0
       0      .1       0     493    .045       0     508      .1       0
Bank Sta=493,508
XS Rating Curve= 0 ,0
Exp/Cntr=0.3,0.1

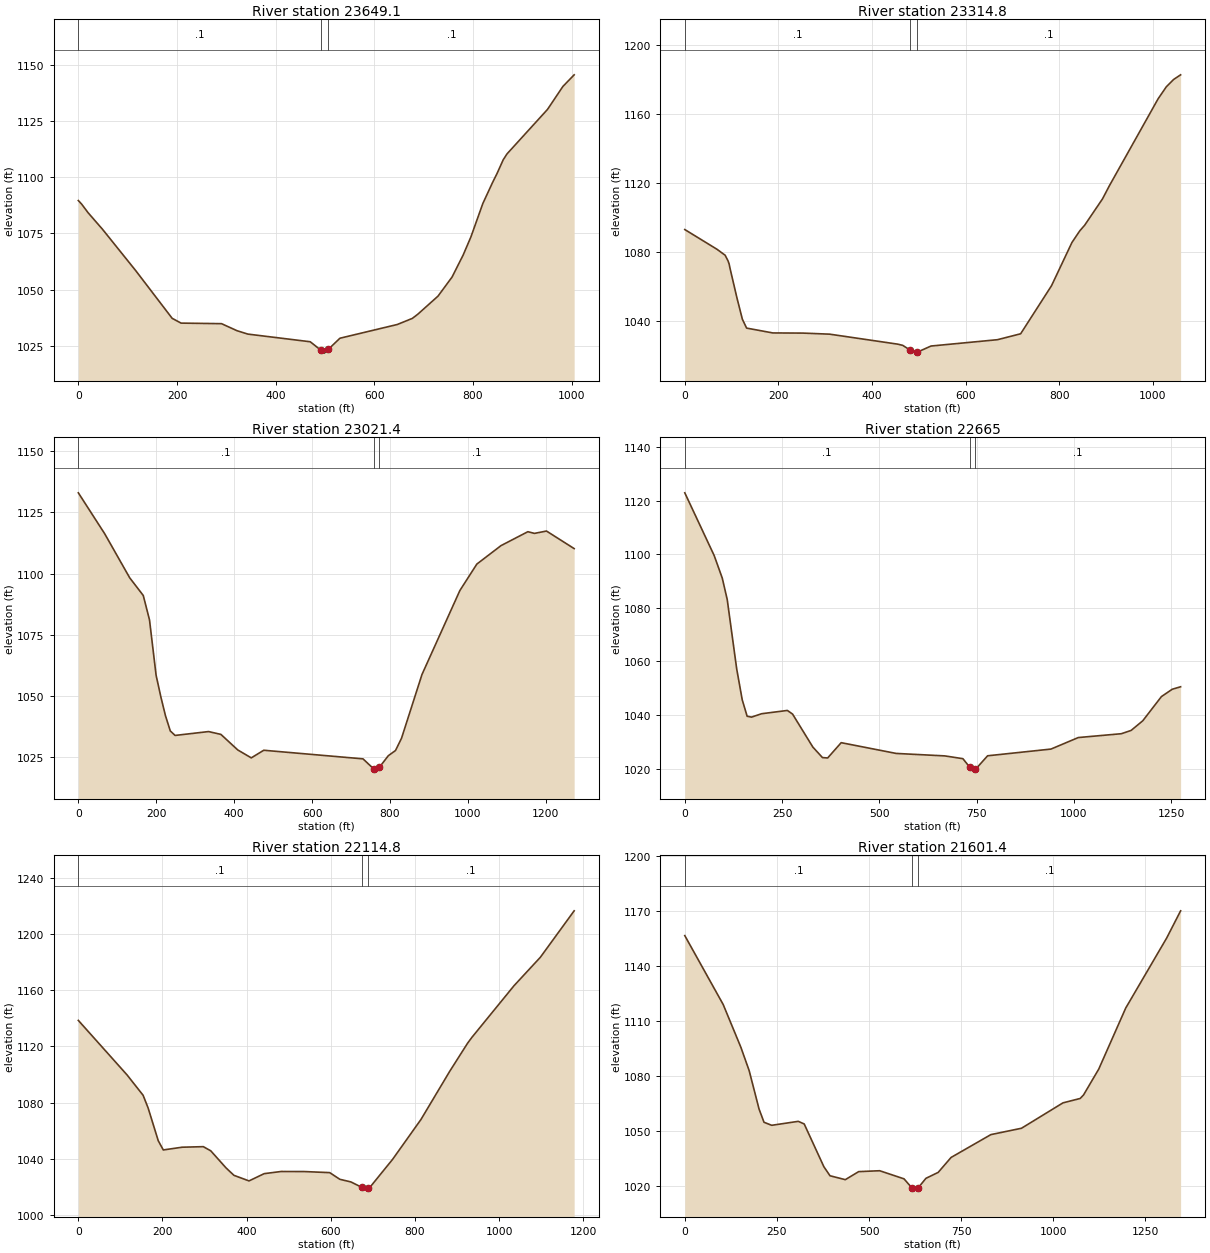
Type RM Length L Ch R = 1 ,23649.1 ,342.293,334.275,325.863
XS GIS Cut Line= 3
     1678368.153       289186.39     1678118.917      288751.517
     1677901.215      288297.374
#Sta/Elev= 30
       0 1089.63     6.6 1088.07    19.8 1084.21    49.1 1076.81   116.2 1058.47
   190.2  1037.2   208.2 1035.08   290.2 1034.83   321.6  1031.7   343.6 1030.19
     470 1026.78   491.9 1022.97   498.6 1021.72   506.9 1023.46   530.2 1028.35
   646.4 1034.46   676.9 1037.17   688.2 1039.07     729 1047.09   757.5  1055.6
   779.9 1065.36   795.7 1073.47   819.9 1088.35   839.2  1097.5   848.3 1101.52
   861.2  1107.8   868.9 1110.41   950.9 1130.19   982.1 1140.41  1004.9 1145.58
#Mann= 3 , 0 , 0
       0      .1       0   491.9    .045       0   506.9      .1       0
Bank Sta=491.9,506.9
XS Rating Curve= 0 ,0
Exp/Cntr=0.3,0.1

Type RM Length L Ch R = 1 ,23314.8 ,289.694,293.409,295.983
XS GIS Cut Line= 3
     1678797.168      288938.971      1678422.21      288626.523
     1678002.689      288239.305
#Sta/Elev= 30
       0 1092.92    68.5 1081.49    86.2 1077.97    92.6 1074.55    94.6 1072.99
    96.3 1070.72   111.5 1053.04     123 1040.73     132  1035.6     188 1032.78
   252.2 1032.69   309.4 1032.07   455.2 1026.24   465.5 1025.55   480.6 1022.94
   492.4 1021.04   495.6 1021.49   525.9 1025.17   667.8 1028.85   717.3 1032.29
   783.3 1060.27   826.9  1085.4   843.7  1092.2     854 1095.41   892.3 1110.82
   906.5 1118.23  1010.9 1168.96  1028.5 1175.96    1044  1180.2    1059 1182.91
#Mann= 3 , 0 , 0
       0      .1       0   480.6    .045       0   495.6      .1       0
Bank Sta=480.6,495.6
XS Rating Curve= 0 ,0
Exp/Cntr=0.3,0.1

Type RM Length L Ch R = 1 ,23021.4 ,349.968,356.437,356.593
XS GIS Cut Line= 3
      1679011.97      288920.904     1678484.359      288330.676
     1678200.105      287942.609
#Sta/Elev= 30
       0 1132.98    67.8 1116.25   131.9 1098.28   166.7 1091.07   182.7  1081.1
   199.6 1058.54     212 1049.56   223.8 1041.92   236.1 1035.77   248.4 1033.94
   334.3 1035.52   365.9 1034.37   409.2 1028.02   443.9 1024.78     476 1027.89
   730.7 1024.38   757.9 1020.33   766.1 1019.37   772.9 1020.98   795.8 1025.68
   814.1 1027.78   829.6  1032.8   882.1 1058.82   979.4 1093.11  1022.9 1103.89
  1084.9 1111.42  1153.9 1117.11  1170.7 1116.42  1201.7 1117.38  1272.7 1110.21
#Mann= 3 , 0 , 0
       0      .1       0   757.9    .045       0   772.9      .1       0
Bank Sta=757.9,772.9
XS Rating Curve= 0 ,0
Exp/Cntr=0.3,0.1

Type RM Length L Ch R = 1 ,22665   ,537.286,550.154,571.537
XS GIS Cut Line= 3
     1679081.393      288849.464     1678794.481       288170.43
      1678464.61      287746.631
#Sta/Elev= 30
       0 1122.89    75.6 1099.47    96.3 1091.08     109 1083.13   133.4 1057.21
   147.6  1045.7   160.2 1039.58   171.5 1039.25   197.3 1040.51   263.6 1041.74
   276.9 1040.39   329.1 1028.08   353.8 1024.16   367.2 1024.02   401.9 1029.72
   543.1 1025.71   668.1 1024.79   714.7 1023.75   731.7 1020.67   741.1 1019.11
   746.7 1019.73   778.2 1024.83     941 1027.33  1011.2 1031.63  1121.9 1033.06
    1147 1034.29  1176.9 1037.88  1224.9 1046.91  1252.6 1049.64  1274.2 1050.57
#Mann= 3 , 0 , 0
       0      .1       0   731.7    .045       0   746.7      .1       0
Bank Sta=731.7,746.7
XS Rating Curve= 0 ,0
Exp/Cntr=0.3,0.1

Type RM Length L Ch R = 1 ,22114.8 ,505.543,513.392,517.7
XS GIS Cut Line= 3
     1679218.828      288889.689     1679312.332      288214.934
     1679427.793      287731.489
#Sta/Elev= 30
       0 1138.53   115.9 1099.65   153.9 1085.19   165.9  1076.1   189.9 1052.82
   201.9 1046.23   246.6 1048.18     297 1048.57   314.6 1045.64     351 1033.44
   369.7 1028.16   405.6 1024.17   441.6 1029.34   481.8 1030.88   537.7 1030.83
   597.4 1030.07   621.4 1025.32   647.6 1023.46   673.7 1019.59   682.7 1018.32
   688.7 1019.22   694.3 1020.15   746.6 1039.47   814.2 1067.95   882.5 1102.25
     925  1122.3   935.2 1126.43  1035.3 1163.24  1097.9  1183.5  1178.2 1216.59
#Mann= 3 , 0 , 0
       0      .1       0   673.7    .045       0   688.7      .1       0
Bank Sta=673.7,688.7
XS Rating Curve= 0 ,0
Exp/Cntr=0.3,0.1

Type RM Length L Ch R = 1 ,21601.4 ,285.955,286.608,286.584
XS GIS Cut Line= 3
     1679483.642      288986.899     1679773.574      288434.067
     1680070.255        287776.8
#Sta/Elev= 30
       0 1156.57   104.2    1119   152.2 1095.67   174.7 1082.93   201.5 1062.01
   214.9  1054.8   235.9 1053.14   307.9  1055.3     324 1053.87   377.4 1030.55
     394 1025.63   435.5  1023.5   471.8 1027.88   528.8 1028.37   594.8 1023.95
   617.6  1018.7   630.3 1018.34   632.6 1018.87   654.2 1024.21   687.6 1027.47
   722.6 1035.62   830.6 1048.07   913.6 1051.53  1026.2 1065.38  1072.8 1067.77
  1081.9 1069.67  1123.3 1083.81  1196.5  1117.1  1307.7 1155.31  1345.4 1170.09
#Mann= 3 , 0 , 0
       0      .1       0   617.6    .045       0   632.6      .1       0
Bank Sta=617.6,632.6
XS Rating Curve= 0 ,0
Exp/Cntr=0.3,0.1

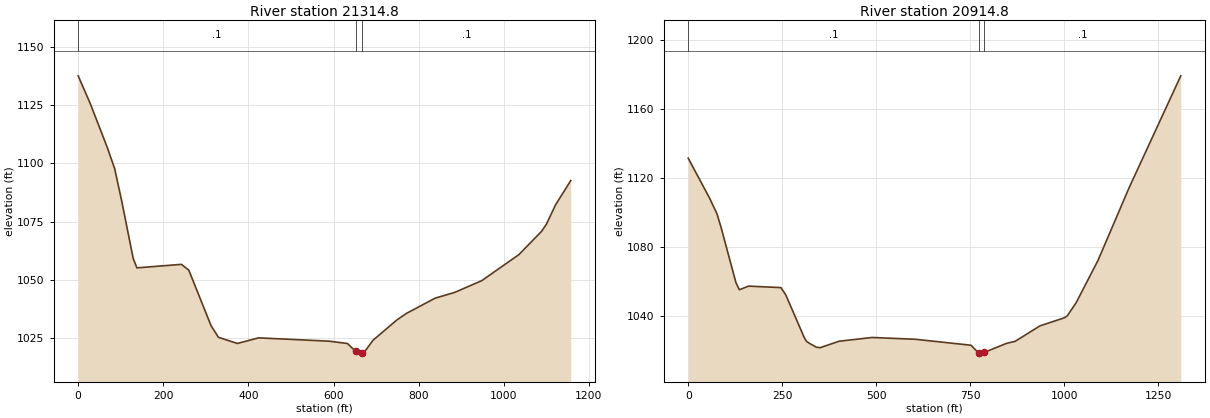
Type RM Length L Ch R = 1 ,21314.8 ,389.549,400,411.888
XS GIS Cut Line= 3
     1679724.991       289084.11     1680049.187       288510.02
     1680254.484      288056.051
#Sta/Elev= 30
       0 1137.52    28.2 1125.73    68.3 1106.86    85.7 1097.79   102.7 1083.54
   129.3 1059.25     138 1055.21   242.6 1056.72     260 1054.22   312.3 1030.43
   329.7 1025.43   374.2 1022.81   423.9 1025.21   589.9 1023.79   632.9 1022.78
   651.8 1019.47   660.9 1018.24   666.8  1018.8     674 1019.48   692.9 1024.19
   748.7 1032.86   771.2 1035.67   838.9 1042.23   885.4 1044.74   948.4 1049.73
  1035.4 1060.85  1089.1  1070.9  1100.5 1073.99  1121.8 1082.22  1157.5 1092.61
#Mann= 3 , 0 , 0
       0      .1       0   651.8    .045       0   666.8      .1       0
Bank Sta=651.8,666.8
XS Rating Curve= 0 ,0
Exp/Cntr=0.3,0.1

Type RM Length L Ch R = 1 ,20914.8 ,393.829,400,420.338
XS GIS Cut Line= 3
      1679771.92      289144.447     1680404.361      288688.949
     1680827.825      288370.117
#Sta/Elev= 30
       0 1131.59      56 1108.78    76.3 1099.41    87.7 1091.18   126.8 1059.45
   135.8 1055.24   160.6 1057.35   246.4 1056.49   259.4 1052.26   307.9 1027.78
   314.4  1025.3     322 1024.16   340.9 1021.87   351.2 1021.64   401.1 1025.35
   489.1 1027.54     604 1026.49   752.1 1023.02   771.9 1018.51     775 1017.87
   786.9 1018.86   846.2 1024.11   869.2 1025.31   935.2 1034.28  1000.4 1038.99
  1008.2 1040.23  1031.1 1047.64  1089.4 1072.26  1171.7 1114.26  1309.5 1179.43
#Mann= 3 , 0 , 0
       0      .1       0   771.9    .045       0   786.9      .1       0
Bank Sta=771.9,786.9
XS Rating Curve= 0 ,0
Exp/Cntr=0.3,0.1