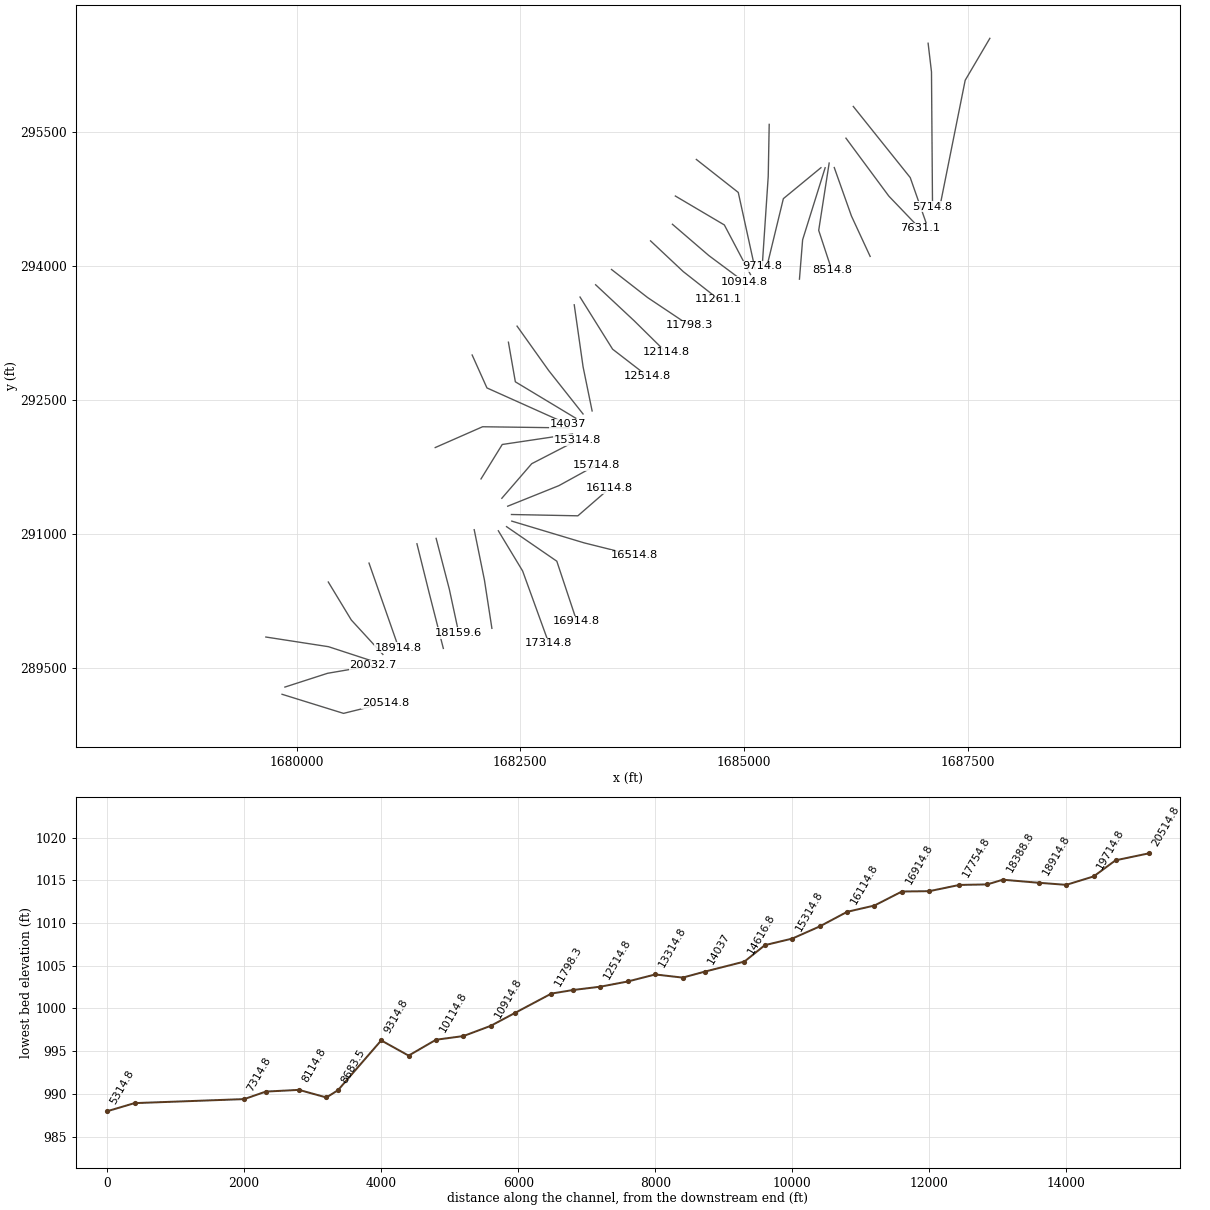
HEC-RAS study SalemFk.prj: SalemFk

--- SalemFk.g01 (geometry) --- (continued)

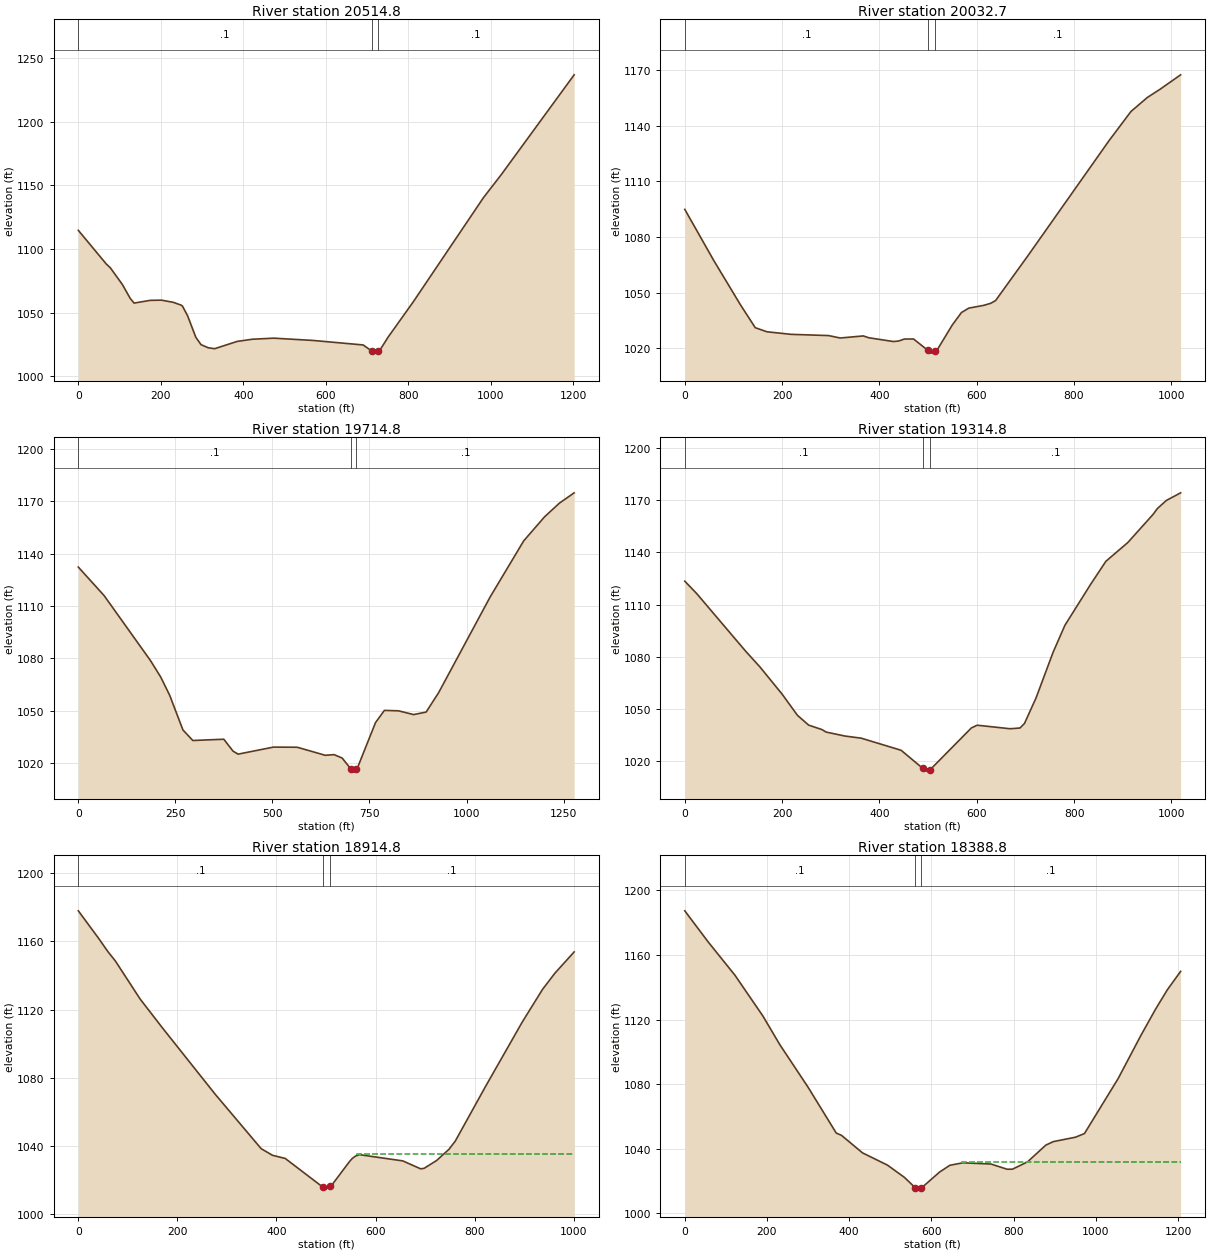
Type RM Length L Ch R = 1 ,20514.8 ,467.883,482.094,480.332
XS GIS Cut Line= 3
      1679835.61      289211.489     1680522.958      288997.998
     1680991.077      289113.618
#Sta/Elev= 30
       0 1114.68    67.5 1088.33    77.9  1085.1   106.7 1072.13   125.7 1061.25
   135.1 1057.49   174.3 1059.65   201.6 1059.79     230 1058.11     249 1055.92
   252.4 1055.14   264.8 1047.57   284.8 1030.62   297.5 1024.79   314.6  1022.4
   330.3 1021.62   385.1 1027.36   421.8 1029.07     474 1029.91   568.8 1028.13
   690.4 1024.58   712.2  1019.6   718.6 1018.15   727.2 1019.98     732 1021.03
   750.6 1030.58   811.5 1058.29   982.1 1140.41    1025 1158.38  1201.9 1236.95
#Mann= 3 , 0 , 0
       0      .1       0   712.2    .045       0   727.2      .1       0
Bank Sta=712.2,727.2
XS Rating Curve= 0 ,0
Exp/Cntr=0.3,0.1

Type RM Length L Ch R = 1 ,20032.7 ,327.388,317.906,306.979
XS GIS Cut Line= 3
     1679867.623      289292.111     1680344.338      289446.096
      1680855.22      289533.424
#Sta/Elev= 30
       0  1094.8    58.8  1067.6   114.2 1043.48   144.8 1031.06   168.9 1028.84
   218.7 1027.46   295.6  1026.8   319.5 1025.49     367 1026.61   378.2 1025.63
   428.6 1023.59   439.6 1023.87   451.4 1024.93   470.3 1024.94   500.1 1018.77
   506.4 1017.34   515.1 1018.56   518.9 1019.11   549.8 1032.47   568.7  1039.2
   583.7 1041.58   614.5 1043.09   628.8 1044.18   638.9 1045.66   704.1 1069.36
   872.3  1131.9   917.2 1147.56   950.8  1155.1   977.1 1159.56  1019.3 1167.32
#Mann= 3 , 0 , 0
       0      .1       0   500.1    .045       0   515.1      .1       0
Bank Sta=500.1,515.1
XS Rating Curve= 0 ,0
Exp/Cntr=0.3,0.1

Type RM Length L Ch R = 1 ,19714.8 ,419.882,400,388.457
XS GIS Cut Line= 3
     1679654.598      289851.735      1680354.98      289743.544
     1680895.431      289566.865
#Sta/Elev= 30
       0 1132.25    66.6 1115.89   186.2 1078.63   212.5 1069.22   235.6 1058.74
   269.5 1039.03   294.9 1032.99   374.8 1033.72   398.5 1026.91   411.6 1025.18
   502.7 1029.21   563.9 1029.13     636 1024.53   658.9  1024.9   679.7 1022.94
   701.2 1016.93   706.5 1015.46   716.2 1016.68   718.7 1017.12   765.6 1043.24
   788.5 1050.23   825.1 1049.97   863.7 1047.83   895.9 1049.26     928  1060.3
    1061  1115.2  1147.4 1147.28  1201.2 1161.06  1239.2 1168.84  1277.3 1174.76
#Mann= 3 , 0 , 0
       0      .1       0   701.2    .045       0   716.2      .1       0
Bank Sta=701.2,716.2
XS Rating Curve= 0 ,0
Exp/Cntr=0.3,0.1

Type RM Length L Ch R = 1 ,19314.8 ,404.682,400,390.808
XS GIS Cut Line= 3
      1680352.76      290466.779     1680610.132      290041.969
     1680963.129      289657.322
#Sta/Elev= 30
       0 1123.51    24.6 1116.36   124.6 1083.47   154.5 1074.26   200.3 1058.55
   231.5  1046.5   254.5 1040.89   282.2 1038.28   290.2  1036.9   329.4  1034.6
   362.5 1033.39   444.5 1026.44   489.2 1016.01   496.4 1014.47   504.2  1015.3
   588.8 1039.26   600.8 1040.83   668.5  1038.8   688.8 1039.23     698 1041.85
   721.9  1056.6   756.8 1082.72     781 1098.17   833.4 1121.49   865.2 1134.93
   910.3 1145.71   962.3 1161.89   970.9 1165.18   989.5 1169.86  1018.8 1174.24
#Mann= 3 , 0 , 0
       0      .1       0   489.2    .045       0   504.2      .1       0
Bank Sta=489.2,504.2
XS Rating Curve= 0 ,0
Exp/Cntr=0.3,0.1

Type RM Length L Ch R = 1 ,18914.8 ,528.124,526.028,524.035
XS GIS Cut Line= 3
     1680808.076      290678.366     1680973.494      290205.992
     1681138.912      289733.618
#Sta/Elev= 30
       0 1177.97    40.7 1161.93    59.6 1154.08    74.9  1148.5   124.9 1126.17
   169.8  1109.3   275.8 1070.56   369.1 1038.45   391.9 1034.56   417.7 1032.71
     493 1016.03     499 1014.71   505.2 1016.29     508 1016.59   511.4 1016.95
   547.2 1030.78   553.4  1032.8   559.7 1034.11   567.3 1034.94   655.1 1031.27
     691 1026.63   697.9 1026.89   723.3  1031.5   748.4 1038.11     761  1042.9
   821.9 1074.84   895.9 1112.57   937.1 1131.87   962.3 1141.44    1001 1153.86
#Mann= 3 , 0 , 0
       0      .1       0     493    .045       0     508      .1       0
#XS Ineff= 2 , 0
                          563.33         1035.18
Permanent Ineff=
       F       F
Bank Sta=493,508
XS Rating Curve= 0 ,0
Exp/Cntr=0.3,0.1

Type RM Length L Ch R = 1 ,18388.8 ,228.994,229.226,228.433
XS GIS Cut Line= 3
     1681344.045      290894.231     1681482.575       290337.09
     1681639.027      289724.357
#Sta/Elev= 30
       0 1187.36    56.9 1168.11   122.2 1147.44     190 1122.26   231.3 1104.49
   299.9 1078.19   368.5 1049.79   381.4 1048.34   432.4 1037.52   493.1 1029.94
   534.4 1022.34   560.4 1016.03   572.6 1015.07   575.4 1015.69   620.1 1025.67
   645.1 1029.84   676.8 1031.37     745 1030.61   784.2 1027.39   797.3 1027.41
     834 1031.95   878.4  1042.3   896.7 1044.48   950.9 1047.23   972.5 1049.48
  1054.3 1083.44  1109.6 1110.11    1146 1126.69  1174.3 1138.51  1206.5 1149.88
#Mann= 3 , 0 , 0
       0      .1       0   560.4    .045       0   575.4      .1       0
#XS Ineff= 2 , 0
                          673.34         1031.98
Permanent Ineff=
       F       F
Bank Sta=560.4,575.4
XS Rating Curve= 0 ,0
Exp/Cntr=0.3,0.1

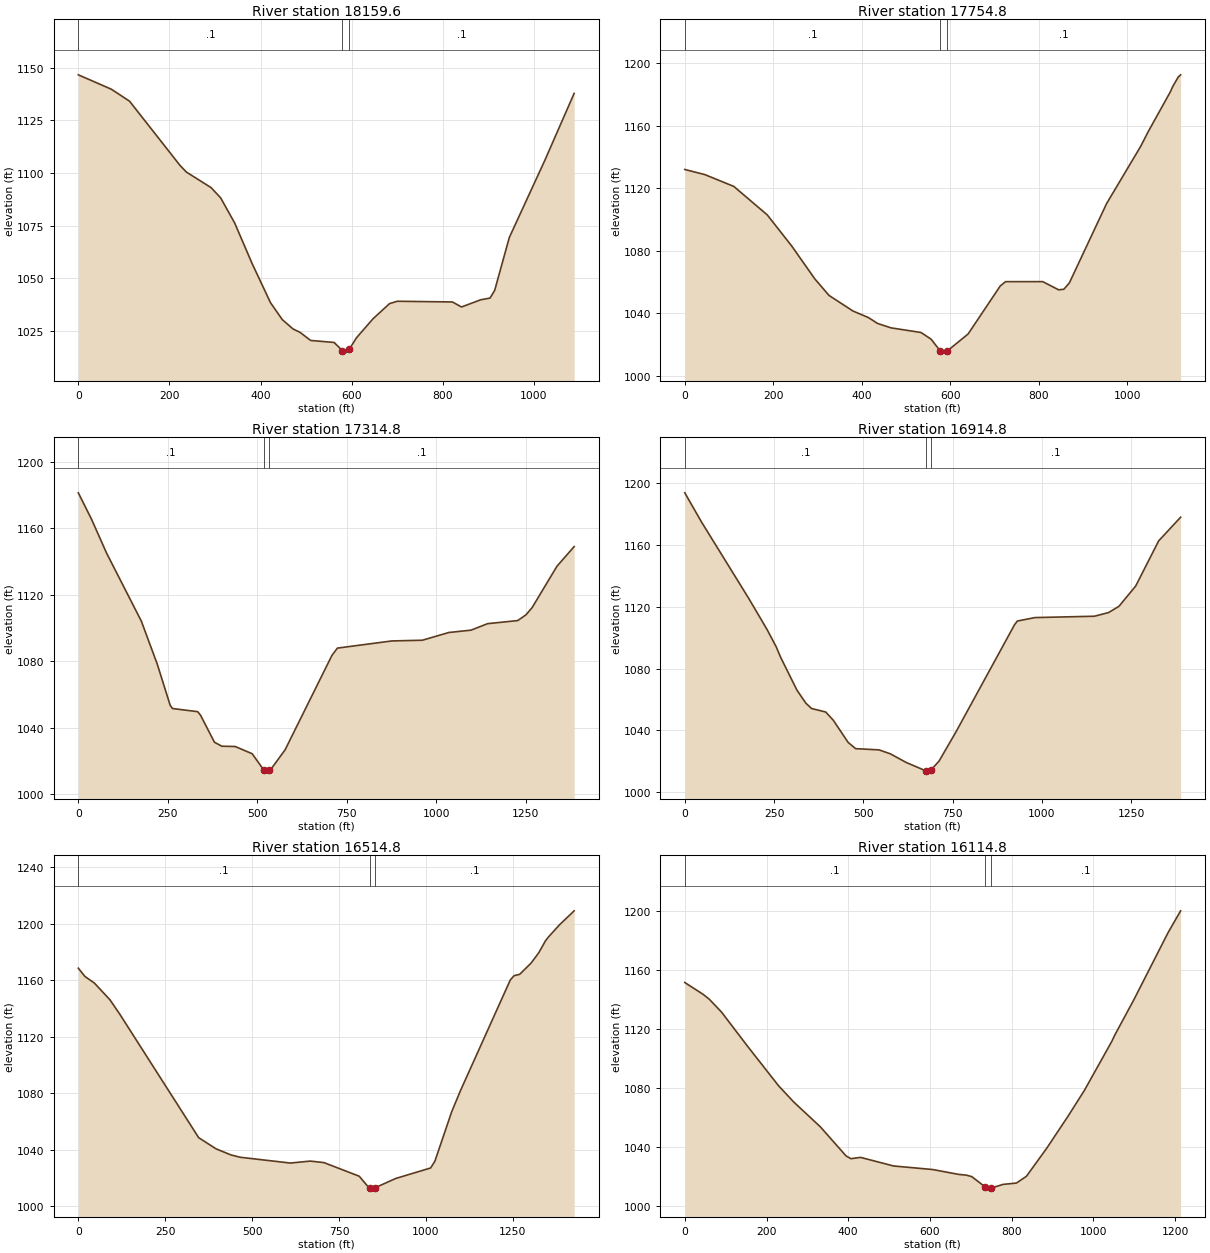
Type RM Length L Ch R = 1 ,18159.6 ,406.482,404.798,403.446
XS GIS Cut Line= 3
     1681558.578      290954.569     1681706.249      290385.791
     1681811.446      289896.472
#Sta/Elev= 30
       0 1146.58    72.3 1139.77   112.3 1134.09   223.4 1103.53   237.2 1100.43
   291.4 1093.05   312.4 1088.18   343.3 1076.19   381.3 1057.06   421.8 1038.43
   447.4 1030.48     471 1026.01   486.3 1024.41   509.8 1020.54   561.3 1019.58
   579.5 1015.72   585.8 1014.52   594.5 1016.29   610.1 1021.72   646.6  1030.8
     683 1038.02   699.9 1039.13     821  1038.8   840.9 1036.42   883.3 1039.85
   903.5 1040.63   913.7  1044.3   945.8 1069.38  1023.5 1105.88  1088.1 1137.79
#Mann= 3 , 0 , 0
       0      .1       0   579.5    .045       0   594.5      .1       0
Bank Sta=579.5,594.5
XS Rating Curve= 0 ,0
Exp/Cntr=0.3,0.1

Type RM Length L Ch R = 1 ,17754.8 ,431.595,439.947,444.336
XS GIS Cut Line= 3
     1681984.291      291051.779     1682098.808      290487.987
     1682182.064      289948.946
#Sta/Elev= 30
       0 1132.06    45.2  1128.8   110.8 1121.22   186.4 1102.98   241.4 1083.16
   293.8 1062.04   325.9 1051.43     380 1041.45   415.4 1037.18   435.4  1033.5
     466 1030.65   533.9 1027.67   556.7  1023.4   577.9  1015.7     587 1014.46
   592.9 1015.76   640.3  1026.7     713 1057.45     725 1060.23   809.1 1060.24
   845.1 1054.99   856.8 1055.37   869.2 1059.41   953.3 1110.18  1030.3 1146.81
  1047.3  1156.2  1097.4 1181.75  1102.8 1185.14  1115.2 1191.21  1120.7 1192.68
#Mann= 3 , 0 , 0
       0      .1       0   577.9    .045       0   592.9      .1       0
Bank Sta=577.9,592.9
XS Rating Curve= 0 ,0
Exp/Cntr=0.3,0.1

Type RM Length L Ch R = 1 ,17314.8 ,385.431,400,399.397
XS GIS Cut Line= 3
      1682254.11      291039.468     1682525.826      290589.864
     1682818.959      289781.342
#Sta/Elev= 30
       0 1181.48    36.7 1165.65    78.8 1145.21     176 1104.16   220.6 1078.19
   256.8 1053.31   263.2 1051.47   333.6 1049.56   341.6 1047.37   380.4 1031.13
   401.1 1028.74   438.2 1028.58   485.8 1024.21   517.8  1014.5   525.3 1013.73
   532.8 1014.59   539.7 1015.34   577.7 1026.56   708.8 1083.56   723.8 1087.88
   876.1  1092.2   961.3 1092.63  1035.4  1097.3  1097.1 1098.69  1143.5 1102.61
  1227.8 1104.48  1250.9 1107.97  1268.1 1112.35  1337.6  1137.3  1385.4 1149.07
#Mann= 3 , 0 , 0
       0      .1       0   517.8    .045       0   532.8      .1       0
Bank Sta=517.8,532.8
XS Rating Curve= 0 ,0
Exp/Cntr=0.3,0.1

Type RM Length L Ch R = 1 ,16914.8 ,397.823,400,423.085
XS GIS Cut Line= 3
      1682345.77      291085.931     1682907.936      290699.397
     1683130.702      290029.395
#Sta/Elev= 30
       0  1193.9    46.5 1175.13   178.8 1125.62   230.4 1105.37   255.7 1094.31
   268.5 1087.34   314.1  1066.1     339 1057.69     355 1054.24   394.5 1051.98
   415.9 1046.62   457.3  1032.3   478.3 1028.24   543.9 1027.45   575.6 1024.89
   620.1 1019.28   674.7 1013.89   680.5 1013.69   689.7 1014.49   711.9 1020.18
   758.8 1038.89   923.3  1108.5   931.3 1110.88   980.2 1113.11    1147 1113.99
  1186.7 1116.38  1215.5 1120.38  1262.5 1133.55  1326.8 1162.77  1388.3 1178.11
#Mann= 3 , 0 , 0
       0      .1       0   674.7    .045       0   689.7      .1       0
Bank Sta=674.7,689.7
XS Rating Curve= 0 ,0
Exp/Cntr=0.3,0.1

Type RM Length L Ch R = 1 ,16514.8 ,396.874,400,421.494
XS GIS Cut Line= 3
     1682404.579      291147.564     1683214.017      290904.337
     1683777.653        290763.5
#Sta/Elev= 30
       0  1168.6      19 1162.73    46.1 1158.07    90.9 1146.23   119.2 1136.03
   346.2  1048.5   396.2  1040.6   438.9 1036.29   465.6 1034.63   609.7 1030.53
   667.1 1031.91   706.4 1030.85   807.9 1021.21   837.7 1012.54   842.1 1012.05
   852.7 1012.92   912.9  1019.6  1013.4 1027.04  1025.7 1031.89  1073.8 1066.77
  1099.1 1081.78  1242.4 1160.18  1253.3 1163.27  1269.6 1164.27  1302.3 1172.22
  1324.5 1179.56  1343.9 1188.08  1352.8 1190.85  1383.8 1199.27  1426.2 1209.24
#Mann= 3 , 0 , 0
       0      .1       0   837.7    .045       0   852.7      .1       0
Bank Sta=837.7,852.7
XS Rating Curve= 0 ,0
Exp/Cntr=0.3,0.1

Type RM Length L Ch R = 1 ,16114.8 ,387.956,400,395.223
XS GIS Cut Line= 3
     1682400.943      291221.669      1683143.41      291207.028
     1683499.158      291515.961
#Sta/Elev= 30
       0 1151.49    45.4 1143.37    60.3 1140.06    89.9 1131.43   154.7 1107.87
   229.8 1081.35   266.2 1070.54   331.8 1053.58   394.6 1033.88   406.5 1031.97
   430.2 1032.85     511 1027.02   606.9  1024.6   671.1 1021.27   688.9 1020.82
   702.3 1019.81   735.1 1012.84   741.7 1011.31   750.1 1012.03     779 1014.52
   811.7 1015.43   836.1    1020   885.8 1039.02   937.9 1060.73   977.8 1078.17
  1045.1 1111.53  1052.1 1115.64  1099.3 1139.89  1182.8 1185.29  1213.6 1200.13
#Mann= 3 , 0 , 0
       0      .1       0   735.1    .045       0   750.1      .1       0
Bank Sta=735.1,750.1
XS Rating Curve= 0 ,0
Exp/Cntr=0.3,0.1

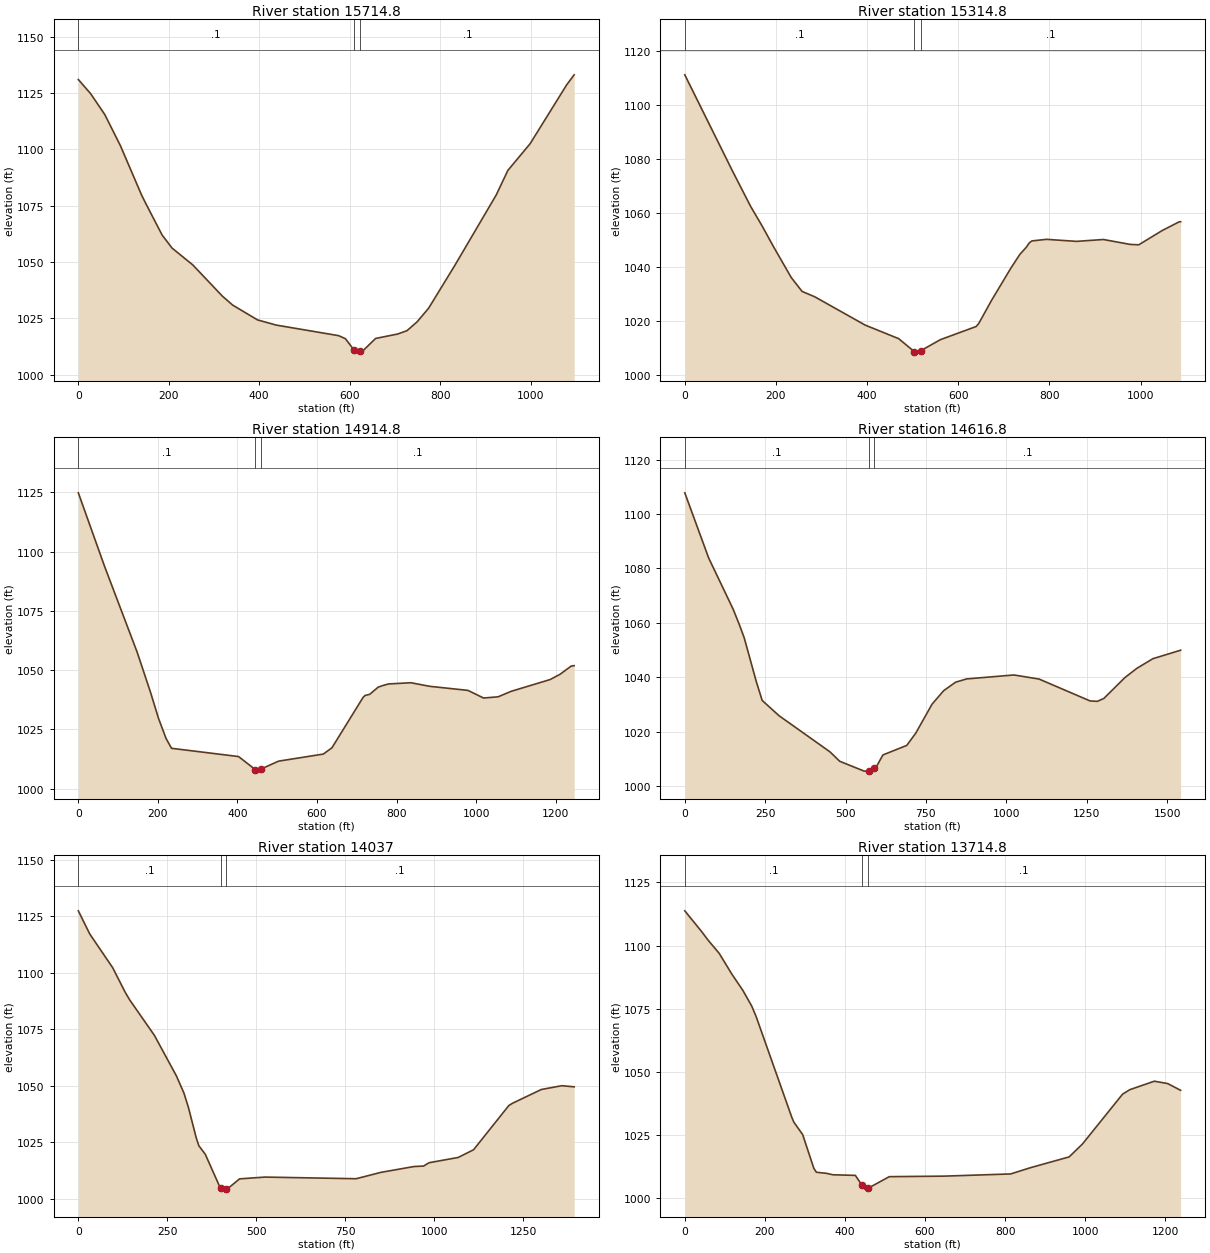
Type RM Length L Ch R = 1 ,15714.8 ,389.256,400,399.195
XS GIS Cut Line= 3
     1682358.924      291314.396     1682930.929      291544.216
      1683351.57      291775.546
#Sta/Elev= 30
       0 1130.97    27.5 1124.62    58.7 1115.36    93.1  1101.6   139.6 1079.85
   148.3 1076.32   185.2 1062.02   207.2 1056.21     253 1048.75   318.4 1034.91
   341.3 1030.91   396.4 1024.33   437.6 1022.04   575.6 1017.35   590.6 1016.01
   608.9 1011.19   616.2  1009.6   623.9 1010.33   631.1 1010.98   657.4 1016.11
   706.2 1018.07   726.8 1019.56     749 1023.44   774.6 1029.51   833.2  1048.7
   924.2 1079.77   949.9 1090.65   999.1 1102.49  1079.9 1128.59  1096.5 1133.05
#Mann= 3 , 0 , 0
       0      .1       0   608.9    .045       0   623.9      .1       0
Bank Sta=608.9,623.9
XS Rating Curve= 0 ,0
Exp/Cntr=0.3,0.1

Type RM Length L Ch R = 1 ,15314.8 ,396.35,400,381.203
XS GIS Cut Line= 3
     1682293.343      291403.172     1682627.422      291789.691
     1683140.208      292054.293
#Sta/Elev= 30
       0 1111.15   104.6 1075.57   144.7  1062.4   170.1  1055.1   193.7 1047.85
   233.6 1036.14   257.3 1031.02   285.3 1029.01   395.9 1018.54   469.3 1013.53
   503.4 1008.77   507.6 1008.18   518.4 1009.14   560.8 1013.16   639.1 1018.02
   644.9 1019.13   673.3 1027.78   715.4 1039.61     735 1044.68   748.7 1047.23
   756.3 1049.05   761.8  1049.7   793.5 1050.28   859.6 1049.53   918.6 1050.22
   976.9 1048.41   996.1 1048.26  1047.4 1053.53  1084.8 1056.77  1087.9 1056.79
#Mann= 3 , 0 , 0
       0      .1       0   503.4    .045       0   518.4      .1       0
Bank Sta=503.4,518.4
XS Rating Curve= 0 ,0
Exp/Cntr=0.3,0.1

Type RM Length L Ch R = 1 ,14914.8 ,312.945,298.048,303.734
XS GIS Cut Line= 3
      1682060.32        291619.5     1682297.855        292004.6
     1683083.196      292121.777
#Sta/Elev= 30
       0 1124.85    66.1 1093.76     148 1057.56   181.6 1040.62   201.4 1029.76
   220.6 1021.17   234.3 1017.04   402.8 1013.56     445 1008.05   449.9 1007.41
     460 1008.35   503.4 1011.62   615.8  1014.6   637.5 1017.24   716.1 1038.58
   721.1 1039.35   732.4 1039.81   753.8 1042.84   764.5 1043.48   779.9  1044.2
     836 1044.71   883.1 1043.21   979.6 1041.48  1018.7 1038.26  1055.3 1038.77
  1088.2 1041.09    1186 1046.05    1211 1048.27    1239 1051.74  1246.5 1051.92
#Mann= 3 , 0 , 0
       0      .1       0     445    .045       0     460      .1       0
Bank Sta=445,460
XS Rating Curve= 0 ,0
Exp/Cntr=0.3,0.1

Type RM Length L Ch R = 1 ,14616.8 ,610.889,579.781,578.661
XS GIS Cut Line= 3
     1681548.521      291970.248     1682077.986      292202.863
     1683041.661      292189.847
#Sta/Elev= 30
       0 1107.78    74.3 1083.82   150.6 1064.95   169.7 1059.31   184.7 1054.53
   222.7 1038.26   240.7 1031.47   292.8 1025.89   451.5 1012.58   481.8 1009.11
     558 1005.49   573.6  1005.6   588.6 1006.64   595.3    1007   616.2 1011.44
   690.3 1014.93   718.5 1019.48   769.1 1030.12   805.2 1035.07   842.3 1038.18
   876.5 1039.38  1023.6 1040.83  1101.9 1039.33  1260.3  1031.3  1282.8 1031.13
  1303.2 1032.19  1368.6 1039.85  1405.9 1043.26  1455.7 1046.81  1542.1 1049.93
#Mann= 3 , 0 , 0
       0      .1       0   573.6    .045       0   588.6      .1       0
Bank Sta=573.6,588.6
XS Rating Curve= 0 ,0
Exp/Cntr=0.3,0.1

Type RM Length L Ch R = 1 ,14037   ,330.724,322.171,323.283
XS GIS Cut Line= 3
     1681961.382       293004.97      1682126.78      292636.891
     1683030.139       292231.71
#Sta/Elev= 30
       0 1127.44      32 1117.23    96.6 1102.27   131.2 1091.56   144.4 1088.03
   213.8 1072.35   275.8 1054.36   296.8 1046.81   309.3 1040.53   331.4    1027
   338.7 1023.52     357 1019.68   396.5 1005.71   400.4 1004.75   415.4 1004.37
   418.2 1004.31   453.2 1008.85   524.8 1009.64   780.8 1008.91   850.3 1011.72
   943.4 1014.31   970.7 1014.52   985.5 1015.98  1067.6 1018.32  1110.9 1021.73
    1210  1041.3  1220.6 1042.32  1301.3 1048.39  1358.6 1050.06  1393.6 1049.57
#Mann= 3 , 0 , 0
       0      .1       0   400.4    .045       0   415.4      .1       0
Bank Sta=400.4,415.4
XS Rating Curve= 0 ,0
Exp/Cntr=0.3,0.1

Type RM Length L Ch R = 1 ,13714.8 ,389.916,400,382.308
XS GIS Cut Line= 3
      1682366.92      293148.199     1682444.352       292705.31
     1683120.062      292298.163
#Sta/Elev= 30
       0 1113.77    42.5 1105.47    57.7 1102.26      86 1096.92   117.8 1088.65
   144.9 1082.31   167.1 1076.09     178    1072   267.4 1031.99   272.4 1030.13
   294.5 1025.18   322.2 1011.89   328.7 1010.29   354.7 1009.84   369.8 1009.29
     426 1009.05   442.1 1005.27   449.6 1003.61   457.1 1003.89   510.7 1008.54
   647.6 1008.75   813.9 1009.62     863 1012.07   960.1 1016.37   993.3 1021.47
  1093.5  1041.2  1111.5 1042.97  1172.8 1046.33  1206.1  1045.4  1238.5 1042.73
#Mann= 3 , 0 , 0
       0      .1       0   442.1    .045       0   457.1      .1       0
Bank Sta=442.1,457.1
XS Rating Curve= 0 ,0
Exp/Cntr=0.3,0.1

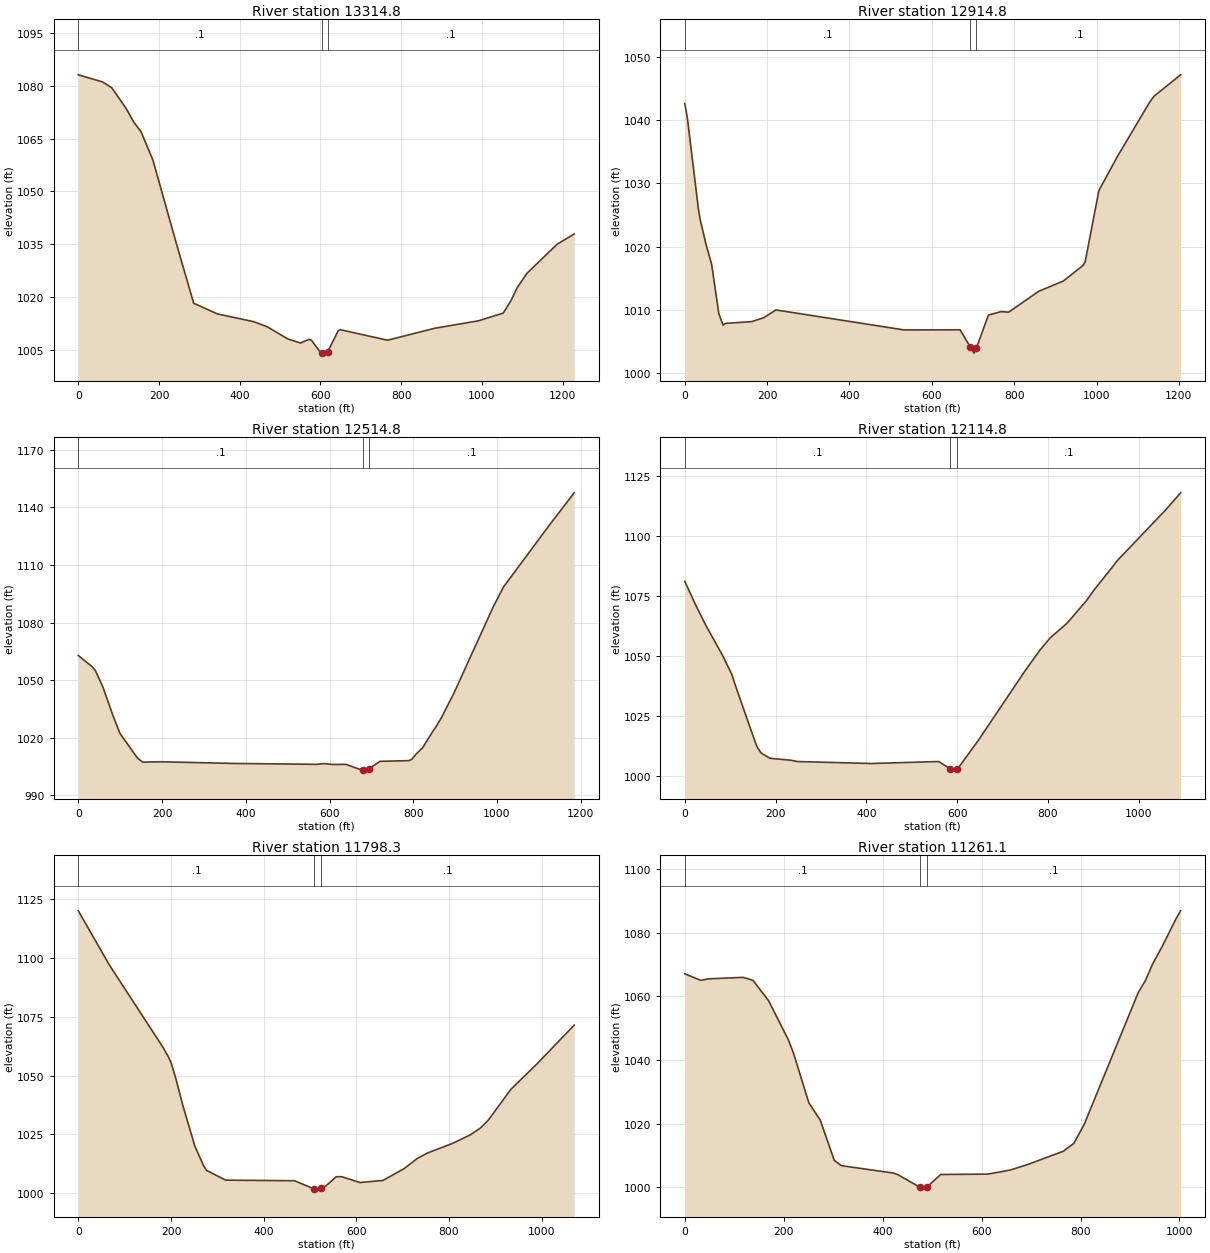
Type RM Length L Ch R = 1 ,13314.8 ,410.643,400,389.561
XS GIS Cut Line= 3
     1682463.638      293327.839     1682817.537       292830.72
     1683201.347      292345.724
#Sta/Elev= 30
       0 1083.11    60.4 1081.08      83 1079.42   118.2 1073.59   137.9 1069.58
   155.3 1066.95   184.8 1058.89   242.7 1035.24   285.9 1018.16   344.7 1015.13
     435 1012.91   467.4 1011.51   519.6 1007.99   550.3 1006.85     571 1007.88
   577.9 1007.62   601.1 1003.98   602.7 1004.03   617.7 1004.32   644.1 1010.37
   648.7 1010.65   766.4 1007.65   883.1 1011.05   991.6 1013.17    1053 1015.37
  1072.1  1018.9  1087.4 1022.55  1111.7 1026.68  1186.4 1034.93  1228.7 1037.85
#Mann= 3 , 0 , 0
       0      .1       0   602.7    .045       0   617.7      .1       0
Bank Sta=602.7,617.7
XS Rating Curve= 0 ,0
Exp/Cntr=0.3,0.1

Type RM Length L Ch R = 1 ,12914.8 ,391.053,400,415.884
XS GIS Cut Line= 3
     1683102.787      293566.475     1683201.677      292872.803
      1683302.68        292379.5
#Sta/Elev= 30
       0 1042.62     6.4 1040.28      33 1025.95    37.1 1024.36      51 1020.49
    65.1 1017.23    82.6 1009.42      93 1007.58    99.4 1007.87   162.7 1008.14
   192.4 1008.78   221.1 1009.99   532.5 1006.83   668.6 1006.85   693.2 1004.15
   702.4 1003.16   708.2 1003.96   737.3 1009.17   767.7 1009.72   786.6 1009.64
   859.8 1012.94   919.5 1014.57   967.7 1017.05   972.5 1017.62  1005.4 1028.76
  1007.6  1029.1  1050.5 1034.23  1128.8 1042.81  1139.9  1043.8  1204.2 1047.16
#Mann= 3 , 0 , 0
       0      .1       0   693.2    .045       0   708.2      .1       0
Bank Sta=693.2,708.2
XS Rating Curve= 0 ,0
Exp/Cntr=0.3,0.1

Type RM Length L Ch R = 1 ,12514.8 ,393.779,400,397.267
XS GIS Cut Line= 3
     1683167.575      293652.991      1683531.51      293070.313
     1683925.157      292766.191
#Sta/Elev= 30
       0 1062.83    31.9  1057.2    40.5 1055.07    58.3 1046.61    82.9 1031.41
    99.6 1022.14   141.7 1009.24   153.8 1007.25   196.8 1007.43   375.9 1006.54
   568.2  1006.1   587.3 1006.46   607.6 1006.02   639.8 1006.08   679.5 1002.91
   684.2 1002.55   694.5  1003.8   720.6 1007.66   789.7 1008.02   796.8 1008.72
   806.8 1011.43   822.2 1014.66   846.9 1023.35   854.2 1025.59   867.1  1030.3
   897.1 1043.16   991.8 1088.52  1015.7 1098.58  1126.9 1131.29  1184.4 1147.63
#Mann= 3 , 0 , 0
       0      .1       0   679.5    .045       0   694.5      .1       0
Bank Sta=679.5,694.5
XS Rating Curve= 0 ,0
Exp/Cntr=0.3,0.1

Type RM Length L Ch R = 1 ,12114.8 ,315.851,316.565,319.781
XS GIS Cut Line= 3
     1683341.883      293790.426      1683774.07      293386.665
     1684130.599      293034.759
#Sta/Elev= 30
       0 1081.07    25.3 1070.75    45.5  1063.1    82.4 1050.59   103.6 1042.42
   110.4  1038.4   145.9 1019.19   158.3 1012.68   161.6  1011.5   168.5 1009.65
   187.6 1007.51   233.9 1006.69   248.3 1006.15   411.1 1005.33   559.4 1006.16
   583.9 1003.23     593 1002.16   598.9 1003.15   605.8 1004.33   647.2  1015.1
   749.9 1043.94   782.3 1052.47     805 1057.58   842.7  1063.8   884.8 1073.05
   901.3 1077.42   944.8 1087.71   951.4 1089.44  1058.1 1110.57  1092.4 1117.93
#Mann= 3 , 0 , 0
       0      .1       0   583.9    .045       0   598.9      .1       0
Bank Sta=583.9,598.9
XS Rating Curve= 0 ,0
Exp/Cntr=0.3,0.1

Type RM Length L Ch R = 1 ,11798.3 ,537.476,537.167,535.634
XS GIS Cut Line= 3
     1683519.543      293961.382     1683924.611      293646.362
     1684387.575       293336.96
#Sta/Elev= 30
       0  1120.1    66.8 1097.12   183.2 1061.89   194.9 1057.83   200.6 1055.26
   210.8 1048.49   225.8 1037.12   251.7 1019.88   271.1 1011.39   276.9 1009.67
   318.1 1005.56   466.5 1005.31   509.6 1001.77   509.9 1001.74   524.6 1002.08
   535.4 1003.29   556.6 1007.02   568.8 1007.01   607.9 1004.53   657.5 1005.44
   703.5 1010.52   730.5 1014.66   753.3 1017.09   807.4 1021.17   846.4 1024.88
   867.3 1027.66   884.5 1031.03   933.8 1044.25   990.7 1055.19    1070 1071.47
#Mann= 3 , 0 , 0
       0      .1       0   509.6    .045       0   524.6      .1       0
Bank Sta=509.6,524.6
XS Rating Curve= 0 ,0
Exp/Cntr=0.3,0.1

Type RM Length L Ch R = 1 ,11261.1 ,345.78,346.267,347.688
XS GIS Cut Line= 3
     1683956.245      294281.049     1684320.911      293938.416
     1684715.536      293628.328
#Sta/Elev= 30
       0 1067.07    32.4 1065.02    47.2 1065.48   117.8 1065.96   137.7 1065.04
   169.4 1058.62   209.4 1046.34   219.8 1042.12   250.8 1026.53   273.8 1021.12
   302.1 1008.52   316.6 1006.82     422 1004.49   430.4 1004.01   474.9 1000.08
   485.2  999.45   489.9 1000.17   517.3 1004.05   612.6 1004.16   657.6 1005.44
   693.1 1007.17   765.4 1011.36   786.5 1013.83   807.3 1019.75   916.8 1061.24
   931.1 1064.96   946.1 1070.27   965.4 1075.77   992.8 1084.31  1002.3 1086.85
#Mann= 3 , 0 , 0
       0      .1       0   474.9    .045       0   489.9      .1       0
Bank Sta=474.9,489.9
XS Rating Curve= 0 ,0
Exp/Cntr=0.3,0.1

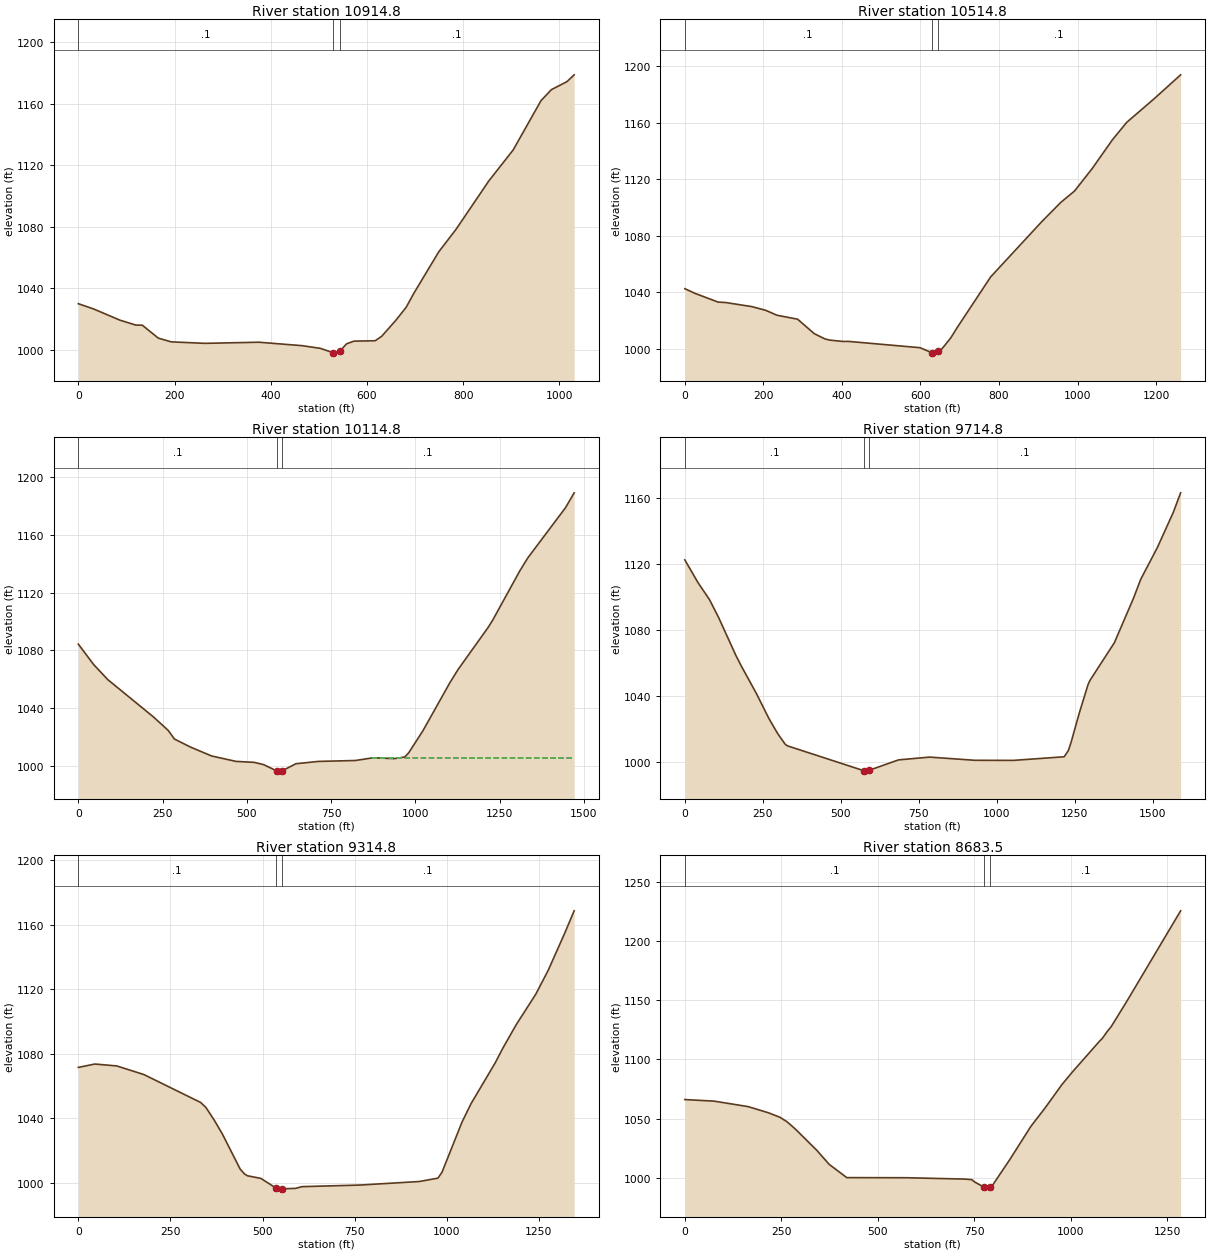
Type RM Length L Ch R = 1 ,10914.8 ,396.149,400,384.856
XS GIS Cut Line= 3
     1684200.688      294466.925     1684607.733      294116.928
     1685004.142      293821.998
#Sta/Elev= 30
       0 1030.08    31.2 1026.73    86.8 1019.35   119.7 1016.19   133.1  1016.1
   166.3 1007.71     193  1005.3     263 1004.32   375.1 1005.06   465.1 1002.82
   502.9  1001.1   529.3  998.31   532.4  997.97   540.9  998.26   544.3   999.4
   557.8 1004.04   573.2 1005.75   617.2 1006.02   630.9 1008.95     660 1019.24
   681.6 1027.75   697.4 1036.73   749.3 1063.75   785.2 1078.34   853.5 1109.84
   904.1 1129.95     962    1162   983.6 1169.14    1016 1174.35  1030.9 1178.76
#Mann= 3 , 0 , 0
       0      .1       0   529.3    .045       0   544.3      .1       0
Bank Sta=529.3,544.3
XS Rating Curve= 0 ,0
Exp/Cntr=0.3,0.1

Type RM Length L Ch R = 1 ,10514.8 ,402.927,400,394.023
XS GIS Cut Line= 3
     1684233.535      294782.641     1684781.277      294459.167
     1685073.282      293904.905
#Sta/Elev= 30
       0 1042.47    25.9 1039.14    84.9 1032.95   104.4 1032.63   171.2 1029.73
   205.8 1027.14   234.6 1023.65   287.3 1020.82   329.7 1010.57   356.8 1006.85
   369.4    1006   401.6 1005.07     418 1005.06   598.7 1000.63   628.6  997.18
   632.6  996.77   643.6  998.07   648.8  998.55     655  999.86   677.3 1007.61
   693.9    1015     779 1050.86   909.9 1090.26   957.4 1103.62   992.6 1111.74
  1037.8  1127.8    1089 1148.06  1125.5 1160.44  1195.9  1177.3  1262.6 1194.09
#Mann= 3 , 0 , 0
       0      .1       0   628.6    .045       0   643.6      .1       0
Bank Sta=628.6,643.6
XS Rating Curve= 0 ,0
Exp/Cntr=0.3,0.1

Type RM Length L Ch R = 1 ,10114.8 ,420.891,400,398.482
XS GIS Cut Line= 3
      1684468.18      295191.594      1684936.86      294822.741
     1685124.244      293968.164
#Sta/Elev= 30
       0 1084.33    45.8  1070.1    87.2 1059.79   223.3 1033.81   266.8 1024.52
   285.3 1018.55   334.1 1012.87   395.5 1006.84   467.6 1003.09     522 1002.41
   549.7 1000.86   588.9  996.46   590.9  996.34   603.9  996.46   645.8 1001.48
   713.2 1003.07   822.1  1003.7   873.9 1005.56   937.8 1005.02   968.9 1006.17
   980.1 1008.97  1022.3 1024.22  1102.8 1057.71  1126.8 1066.74  1215.8 1095.82
  1230.5 1101.33    1310 1135.07  1333.9 1144.13  1445.8  1178.9  1471.3 1189.16
#Mann= 3 , 0 , 0
       0      .1       0   588.9    .045       0   603.9      .1       0
#XS Ineff= 2 , 0
                          870.15         1005.52
Permanent Ineff=
       F       F
Bank Sta=588.9,603.9
XS Rating Curve= 0 ,0
Exp/Cntr=0.3,0.1

Type RM Length L Ch R = 1 ,9714.8  ,417.858,400,446.847
XS GIS Cut Line= 3
     1685282.735      295583.787     1685271.873       295002.57
     1685204.626      293997.388
#Sta/Elev= 30
       0  1122.7    42.8 1108.74    78.9 1098.67   107.8 1087.95   163.3 1064.87
   182.3 1057.84   229.4 1041.61   269.4 1026.47   297.7 1017.24   321.4 1010.87
   328.5 1009.85   573.8  994.73   577.9  994.48   588.8  994.88     685 1001.31
   784.5 1002.99     929 1001.06  1052.2 1000.99  1215.7  1003.2  1229.2 1007.05
  1237.6  1011.9  1263.9 1029.65  1291.8 1046.87    1298 1049.48  1376.4 1072.42
  1437.1 1099.13  1460.9 1110.91  1513.9 1130.07  1565.2 1151.52  1588.7 1163.39
#Mann= 3 , 0 , 0
       0      .1       0   573.8    .045       0   588.8      .1       0
Bank Sta=573.8,588.8
XS Rating Curve= 0 ,0
Exp/Cntr=0.3,0.1

Type RM Length L Ch R = 1 ,9314.8  ,622.15,631.329,584.681
XS GIS Cut Line= 3
     1685861.211      295099.287     1685441.041      294753.354
     1685252.259      293974.376
#Sta/Elev= 30
       0 1071.64    44.7 1073.73   104.2 1072.56   177.8 1067.23   331.9 1049.95
   346.2 1046.88   368.6  1039.1   391.3 1030.26   439.2  1008.7   451.1 1005.64
   459.2 1004.52   495.5  1002.9   536.8  996.88   541.2  996.26   551.8  996.46
   589.5  996.71   606.7  997.79   764.5  998.78   925.6 1000.98   976.1 1003.07
     987 1006.68  1041.6 1037.87  1066.1 1049.26  1131.4 1074.41  1151.7 1083.33
    1188  1097.9  1242.1 1117.14  1275.9 1132.04  1320.8  1155.1  1345.8 1168.61
#Mann= 3 , 0 , 0
       0      .1       0   536.8    .045       0   551.8      .1       0
Bank Sta=536.8,551.8
XS Rating Curve= 0 ,0
Exp/Cntr=0.3,0.1

Type RM Length L Ch R = 1 ,8683.5  ,164.644,168.671,184.172
XS GIS Cut Line= 3
     1685908.284      295098.721     1685656.486      294293.533
     1685621.006      293853.188
#Sta/Elev= 30
       0  1066.1    75.7 1064.78   164.3 1060.14   216.3 1054.99   246.2 1051.19
   264.8 1047.42   285.7 1041.47   342.4 1023.17   374.1 1011.42   419.9 1000.15
   576.8 1000.05   727.2   998.9     744  998.44   751.3   996.5   775.9  992.03
   781.3  990.43   790.9  991.99   793.8  992.31   797.4  993.49   843.1 1015.67
   896.7 1043.23   934.5 1059.22   977.5 1078.68  1005.2 1089.54  1076.1 1115.76
  1081.8 1117.52  1095.3 1123.69  1105.6 1127.78  1147.3 1149.86  1285.4 1225.55
#Mann= 3 , 0 , 0
       0      .1       0   775.9    .045       0   790.9      .1       0
Bank Sta=775.9,790.9
XS Rating Curve= 0 ,0
Exp/Cntr=0.3,0.1

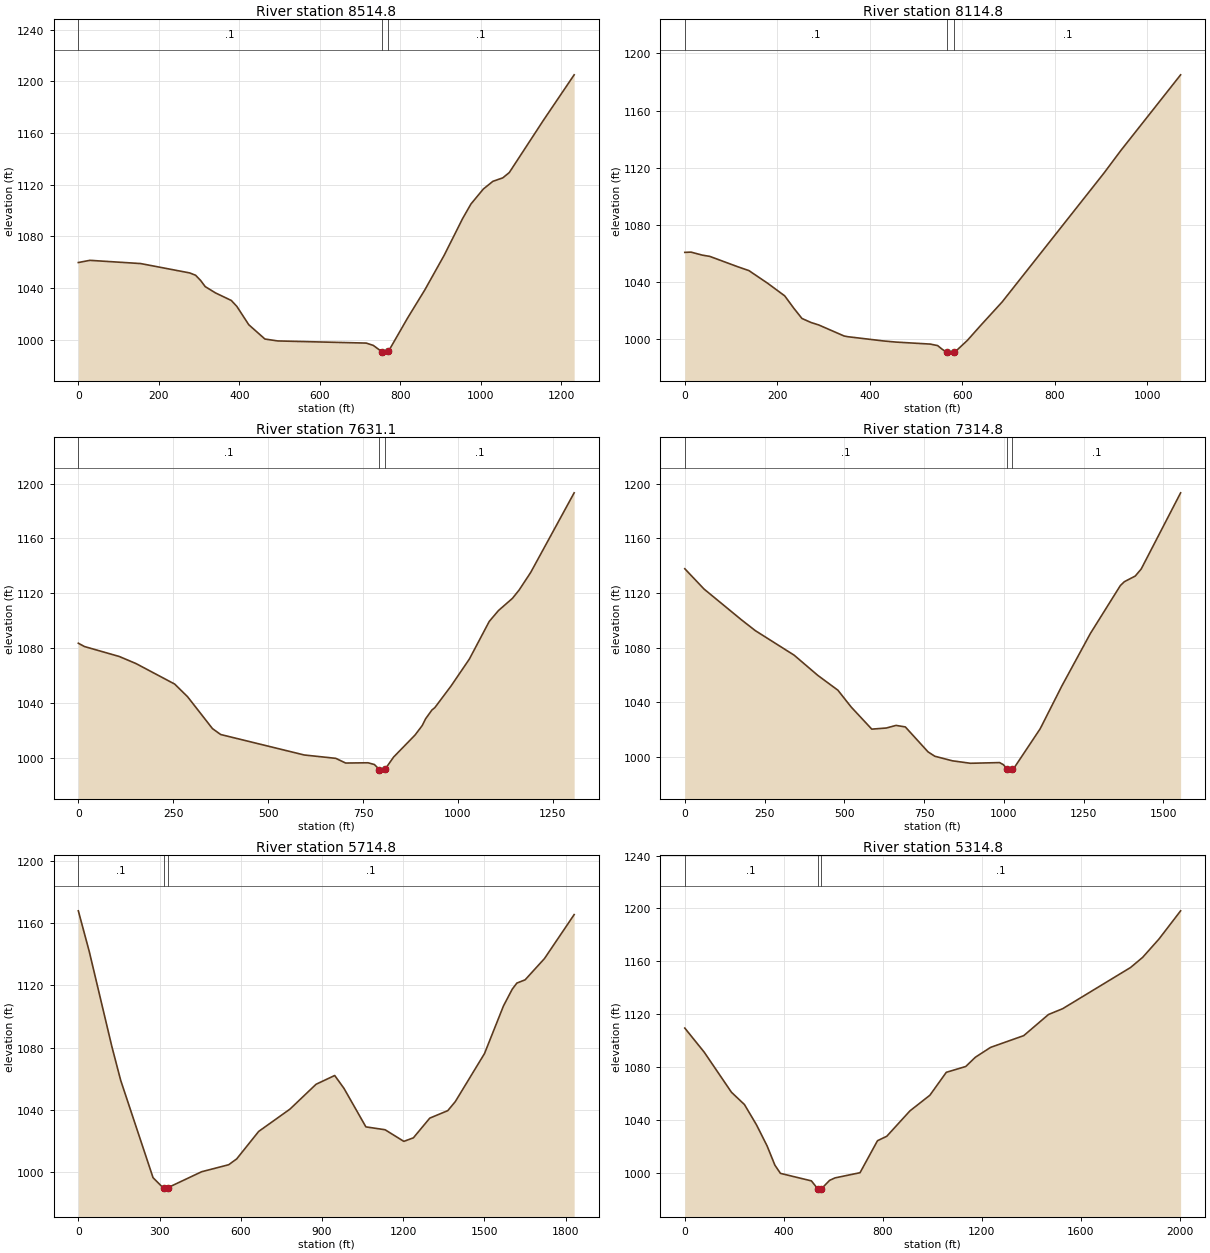
Type RM Length L Ch R = 1 ,8514.8  ,388.008,400,402.617
XS GIS Cut Line= 3
     1685953.151      295151.369     1685836.217      294398.516
      1685982.97      293951.976
#Sta/Elev= 30
       0 1059.69    28.7 1061.39   154.9 1058.89   276.6 1051.65   291.3 1049.86
   303.7 1045.86   315.3 1041.04   340.7  1036.2   380.1 1030.32   393.8 1025.76
   423.5 1011.55   463.6 1000.49   495.4  999.01   715.3  997.35   732.9  995.55
   754.4  990.61     759  989.58   769.4  991.39   772.2  991.88   817.8 1016.61
   860.9 1038.53   909.5 1065.61   954.6 1093.62   975.5    1105  1006.3 1116.58
  1029.9 1122.52  1054.6 1125.21  1070.7 1129.31  1155.3 1169.66  1231.9 1204.95
#Mann= 3 , 0 , 0
       0      .1       0   754.4    .045       0   769.4      .1       0
Bank Sta=754.4,769.4
XS Rating Curve= 0 ,0
Exp/Cntr=0.3,0.1

Type RM Length L Ch R = 1 ,8114.8  ,477.09,483.774,490.546
XS GIS Cut Line= 3
     1686010.136      295101.088      1686202.23      294559.206
     1686411.442      294107.503
#Sta/Elev= 30
       0 1060.89    13.3 1061.08    37.9 1058.97    54.1 1058.09   115.1 1050.78
   138.7 1048.16     179 1039.36   216.2 1030.49   235.6 1021.96   253.4 1014.71
     273 1011.89   289.8 1010.16   344.5 1002.46   352.8 1001.94   429.9  998.98
   456.4   998.2   531.3  996.78   547.1  995.72   556.4  993.28   567.4  990.92
   572.5  991.32   579.7  990.47   582.4  991.02   586.2   991.8   611.1   999.3
   641.5 1010.32   686.6 1026.25   906.9 1116.34   943.9 1132.33  1072.7    1185
#Mann= 3 , 0 , 0
       0      .1       0   567.4    .045       0   582.4      .1       0
Bank Sta=567.4,582.4
XS Rating Curve= 0 ,0
Exp/Cntr=0.3,0.1

Type RM Length L Ch R = 1 ,7631.1  ,315.359,316.226,307.058
XS GIS Cut Line= 3
     1686140.867      295429.592     1686620.584       294781.48
     1686966.522      294420.445
#Sta/Elev= 30
       0 1083.59    16.2 1081.17   107.7 1073.93     152 1068.75   253.9 1053.78
   287.8 1044.56   353.5 1021.27   375.1 1016.98   595.3 1002.04   678.3   999.6
   704.3  996.17   763.2  996.36   780.1  995.09   793.5   991.3   797.1  990.27
   808.5  991.77   830.8 1000.57   887.3 1016.64   906.3 1023.62   914.8 1028.37
   931.6 1034.85   939.4 1036.62   981.9 1052.33  1030.4 1072.08  1082.7  1099.5
    1107 1107.43  1143.8 1116.33  1161.4  1122.4  1191.9 1135.23  1306.4 1193.32
#Mann= 3 , 0 , 0
       0      .1       0   793.5    .045       0   808.5      .1       0
Bank Sta=793.5,808.5
XS Rating Curve= 0 ,0
Exp/Cntr=0.3,0.1

Type RM Length L Ch R = 1 ,7314.8  ,1612.387,1600,1592.988
XS GIS Cut Line= 3
     1686222.952      295784.142     1686859.702      294988.737
     1687036.913      294483.278
#Sta/Elev= 30
       0 1137.75    60.3 1122.87     178 1100.24   221.2 1092.36   342.8 1074.39
   416.9  1059.6     480 1048.71   521.8 1036.34   586.2 1020.17   631.8 1020.99
   662.2 1022.91   691.4  1021.8   762.7 1003.48   783.9  1000.3   838.9  996.96
   895.6  995.14     987  995.65   998.7  994.13  1011.4   990.8    1021  989.39
  1026.4   990.6  1033.7  992.19  1114.2 1020.45  1182.1  1051.8  1271.4 1090.22
  1365.5 1125.41    1378 1128.23  1412.3 1132.41  1430.9 1137.56  1554.5  1193.4
#Mann= 3 , 0 , 0
       0      .1       0  1011.4    .045       0  1026.4      .1       0
Bank Sta=1011.4,1026.4
XS Rating Curve= 0 ,0
Exp/Cntr=0.3,0.1

Type RM Length L Ch R = 1 ,5714.8  ,414.63,400,395.677
XS GIS Cut Line= 3
     1687059.601      296491.115     1687097.293      296170.793
     1687108.885      294661.852
#Sta/Elev= 30
       0    1168    40.6 1141.66   123.7 1080.78   156.5  1058.9     276  996.28
     315  989.46   323.8  988.92     330  989.79   455.4  1000.1   555.4 1004.62
     585 1008.37   666.1 1026.04   781.6 1040.38   878.1 1056.39     947 1062.04
   981.3 1053.74  1062.2 1028.98  1132.9 1027.14  1202.4 1019.66  1237.6 1021.92
  1298.3 1034.62  1364.7 1039.42  1392.3  1045.2  1500.3 1076.14  1570.5 1106.85
  1602.8 1117.58    1620 1121.52  1650.4  1123.6  1721.9 1137.29  1831.5 1165.57
#Mann= 3 , 0 , 0
       0      .1       0     315    .045       0     330      .1       0
Bank Sta=315,330
XS Rating Curve= 0 ,0
Exp/Cntr=0.3,0.1

Type RM Length L Ch R = 1 ,5314.8  ,397.747,400,394.781
XS GIS Cut Line= 3
     1687749.864      296545.833     1687474.045      296076.713
     1687187.299      294645.684
#Sta/Elev= 30
       0 1109.64    78.5 1091.43   188.6 1061.15   241.1 1051.87     290 1036.45
   332.6 1020.62   364.2 1006.04   386.6  999.86   511.6  994.21   536.7  988.33
   546.4  987.97   551.7  988.15   585.1  994.58     607  996.45   708.1 1000.38
   778.7 1024.54   816.2  1027.9   909.8 1047.08   990.4  1058.9  1056.7 1076.21
  1135.4 1080.62  1174.1 1087.59  1235.7 1095.06  1369.8 1103.94  1469.6 1119.88
  1527.2  1124.3  1801.2 1155.38  1850.1 1163.04  1915.8 1176.81  2003.7 1198.22
#Mann= 3 , 0 , 0
       0      .1       0   536.7    .045       0   551.7      .1       0
Bank Sta=536.7,551.7
XS Rating Curve= 0 ,0
Exp/Cntr=0.3,0.1