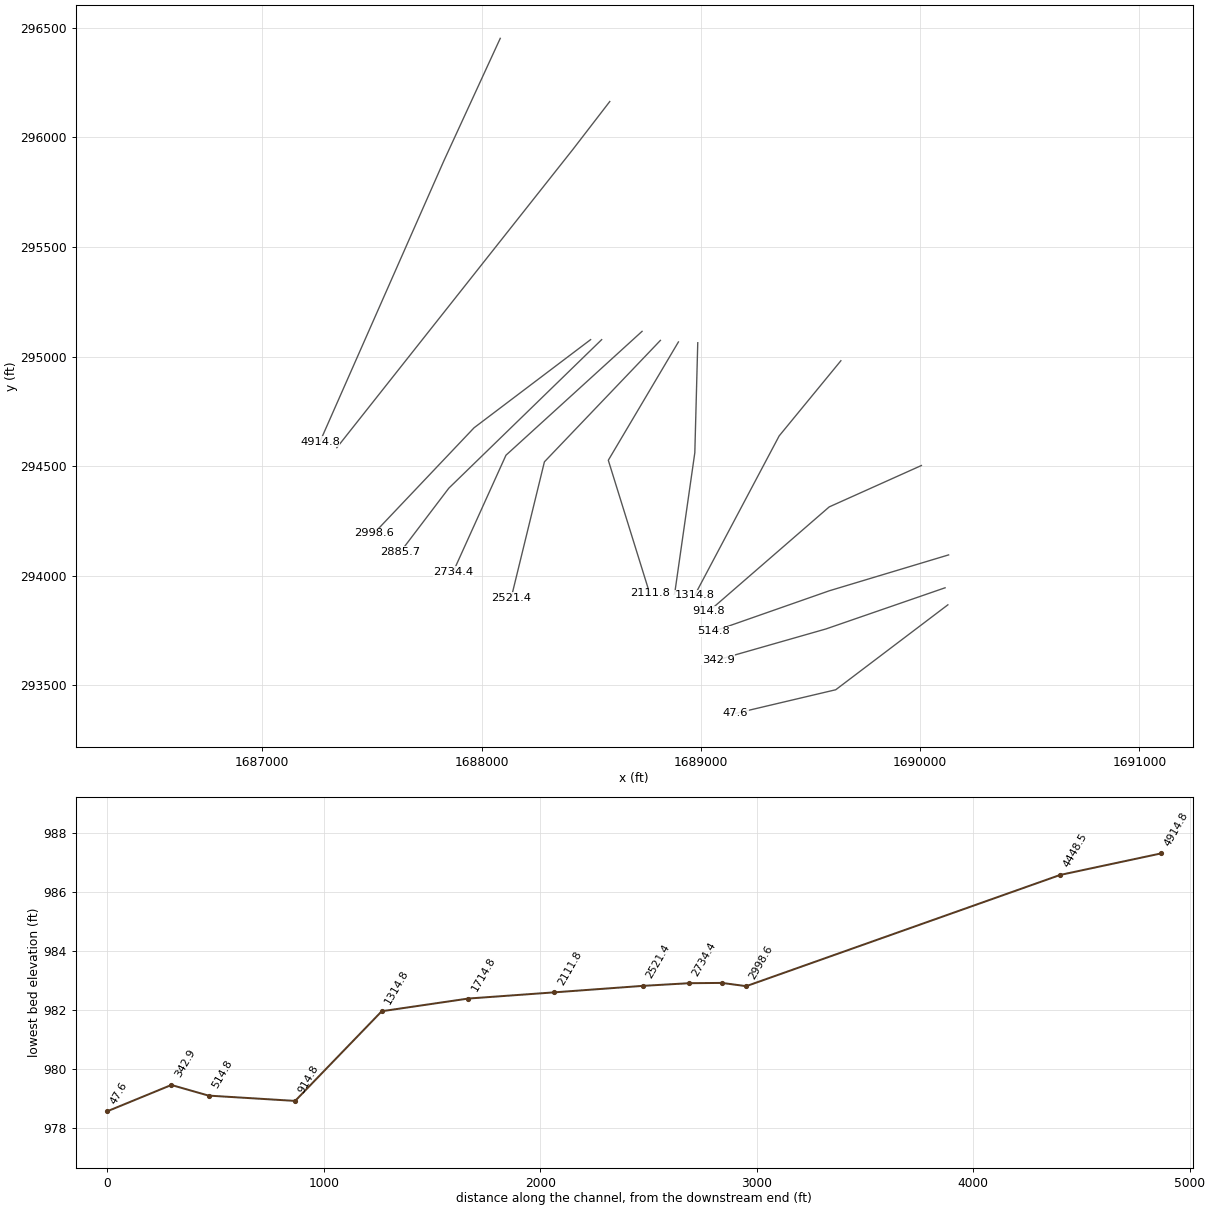
HEC-RAS study SalemFk.prj: SalemFk

--- SalemFk.g01 (geometry) --- (continued)

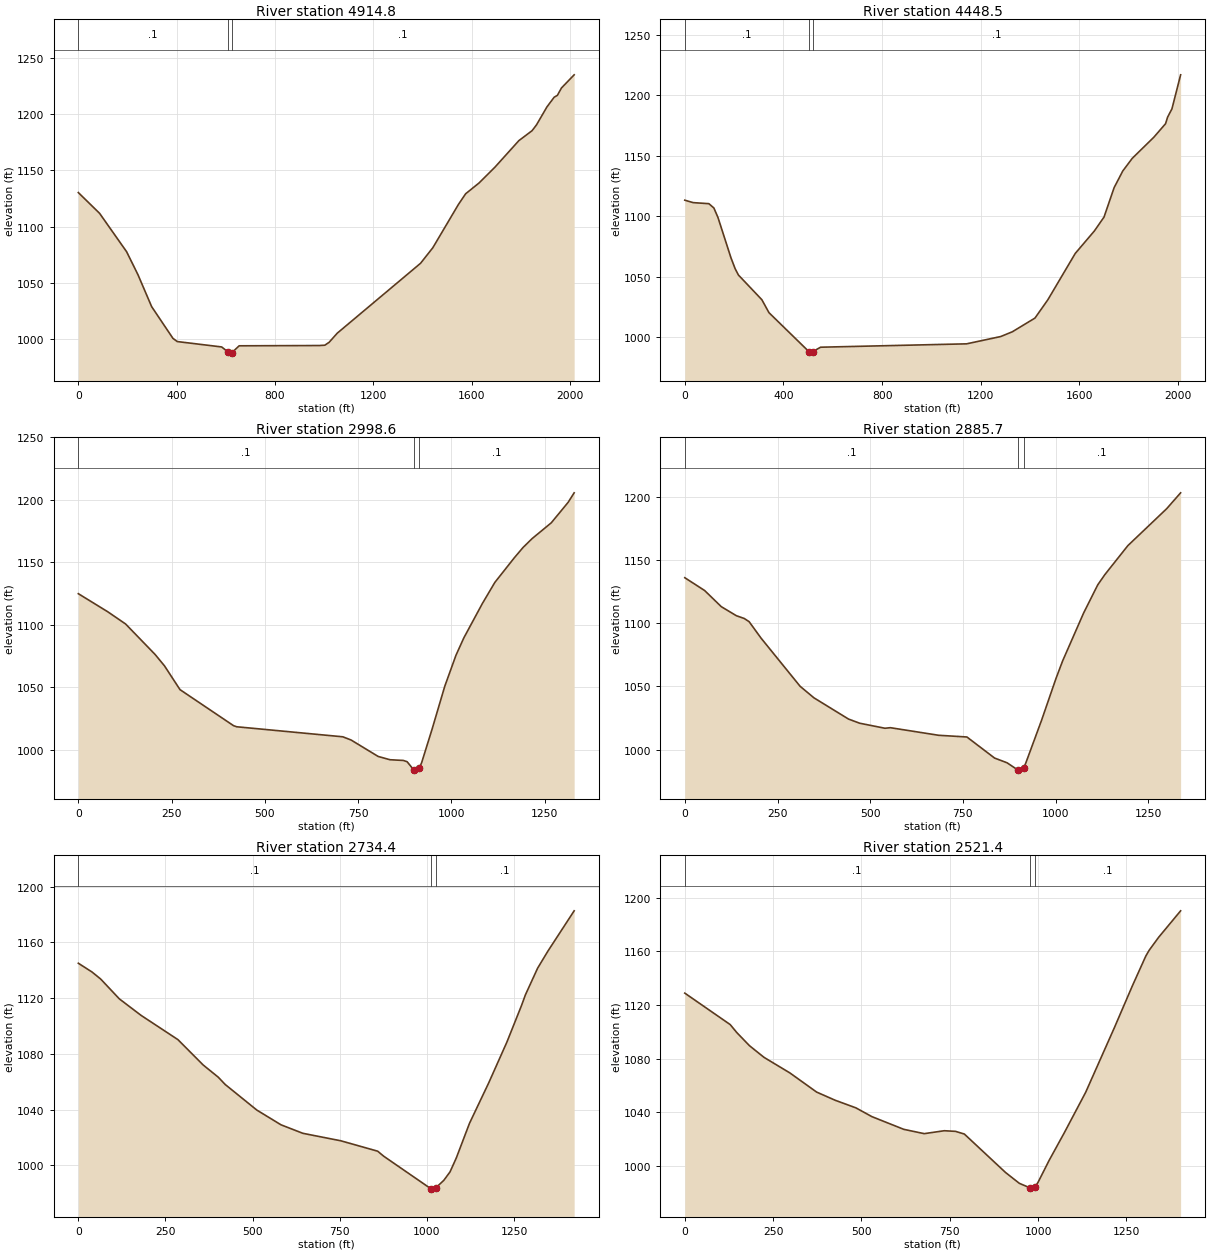
Type RM Length L Ch R = 1 ,4914.8  ,471.739,466.33,460.558
XS GIS Cut Line= 3
     1688085.072      296451.975     1687827.536      295892.303
     1687262.594      294611.139
#Sta/Elev= 30
       0 1130.33    86.5 1111.82   196.3 1077.65   242.2  1057.3   298.1 1028.74
   384.9 1000.42   402.4  997.61   582.8  992.82   608.6  988.39   616.1  987.31
   623.6  987.54     654  993.83   980.5  994.07  1002.4  994.37    1020  996.97
  1052.7 1005.03  1391.7 1067.34  1441.6  1081.2  1545.8 1119.78    1575 1129.25
  1629.7  1138.9  1694.4 1153.01  1791.6 1176.62  1845.1 1185.43  1863.1  1190.6
    1906 1206.76  1935.1 1215.26  1948.1 1216.93  1964.8 1223.53  2016.3 1235.21
#Mann= 3 , 0 , 0
       0      .1       0   608.6    .045       0   623.6      .1       0
Bank Sta=608.6,623.6
XS Rating Curve= 0 ,0
Exp/Cntr=0.3,0.1

Type RM Length L Ch R = 1 ,4448.5  ,1451.98,1449.951,1447.923
XS GIS Cut Line= 3
     1688584.531      296163.697     1688416.782      295945.853
     1687339.752      294584.527
#Sta/Elev= 30
       0 1113.21      34 1111.18    97.6 1110.32   117.9 1106.77   134.4    1099
   187.3 1065.46   204.1 1056.53   217.4 1051.27   312.6 1030.78   341.3 1020.09
   504.3  987.64   510.9  986.58   519.3  987.83   550.7  991.48    1143  994.27
  1281.1 1000.31  1328.3 1004.25  1420.1  1015.6  1472.4 1030.76  1583.5 1069.13
    1661 1087.71  1700.2 1099.25  1741.1 1123.59  1776.2 1137.39  1814.7 1147.87
  1901.8 1165.25  1949.8 1176.56  1957.8 1181.87  1975.6 1188.84  2010.8    1217
#Mann= 3 , 0 , 0
       0      .1       0   504.3    .045       0   519.3      .1       0
Bank Sta=504.3,519.3
XS Rating Curve= 0 ,0
Exp/Cntr=0.3,0.1

Type RM Length L Ch R = 1 ,2998.6  ,113.975,112.849,111.723
XS GIS Cut Line= 3
      1688497.08      295077.421     1687965.727      294675.382
      1687509.66      294194.257
#Sta/Elev= 30
       0 1124.87      79 1110.37   126.7 1100.62   205.5 1076.31   230.9 1067.13
   272.6 1048.05   416.1  1019.2   424.3 1018.33     709 1010.29   731.3 1007.71
   803.9  994.54   835.6  991.93   871.5  991.35   881.5  990.31   898.8  983.93
   906.7  982.81   913.8     985   920.4  989.62   948.7 1016.77   982.3 1050.71
  1012.4  1075.6  1033.7 1089.63  1083.5 1117.18  1116.7 1133.94  1168.4 1153.47
  1192.2 1161.86  1216.3 1168.91  1267.9 1181.63    1313 1197.98  1329.2 1205.62
#Mann= 3 , 0 , 0
       0      .1       0   898.8    .045       0   913.8      .1       0
Bank Sta=898.8,913.8
XS Rating Curve= 0 ,0
Exp/Cntr=0.3,0.1

Type RM Length L Ch R = 1 ,2885.7  ,142.543,151.265,159.987
XS GIS Cut Line= 3
      1688547.56      295077.421     1687850.457      294399.737
     1687629.942      294109.058
#Sta/Elev= 30
       0 1135.85    53.5 1125.72    98.5 1112.94   138.9 1105.83   160.4  1103.6
   173.5 1101.09   205.7 1088.06   310.9 1050.02   348.4 1040.85   441.5 1024.09
   471.6  1020.8   539.7 1016.82   554.4 1017.26   684.3 1011.27   760.8 1009.91
   835.4  993.25   868.9  989.54   898.4  983.77   902.7  982.92   913.4  985.27
   919.3  989.09   962.2 1023.21  1001.1 1056.26  1018.9 1070.06  1075.6    1108
  1113.8 1130.31    1133 1138.38  1194.8 1161.21  1299.6 1190.45  1337.1 1202.97
#Mann= 3 , 0 , 0
       0      .1       0   898.4    .045       0   913.4      .1       0
Bank Sta=898.4,913.4
XS Rating Curve= 0 ,0
Exp/Cntr=0.3,0.1

Type RM Length L Ch R = 1 ,2734.4  ,208.892,213.073,217.254
XS GIS Cut Line= 3
     1688731.812      295115.281     1688111.067      294550.089
     1687870.646      294018.727
#Sta/Elev= 30
       0 1145.03    38.9  1138.8    64.1  1133.7   117.6 1119.47     180 1107.61
   285.8  1090.2   358.1 1072.03   401.4 1063.27   421.4 1058.01   512.2 1039.64
   581.7 1029.05   644.2 1022.97   753.2  1017.6     859 1010.13   876.1 1006.55
  1010.9  983.32  1013.6  982.91  1022.2  982.99  1025.9  983.89  1048.7  989.22
  1066.6  995.31  1084.6 1005.31  1122.3 1030.08  1178.2 1059.52    1230  1088.6
  1271.9 1114.83  1282.9 1122.39  1317.9 1141.49  1347.2 1153.65  1422.7 1182.64
#Mann= 3 , 0 , 0
       0      .1       0  1010.9    .045       0  1025.9      .1       0
Bank Sta=1010.9,1025.9
XS Rating Curve= 0 ,0
Exp/Cntr=0.3,0.1

Type RM Length L Ch R = 1 ,2521.4  ,397.487,409.533,421.579
XS GIS Cut Line= 3
      1688815.45      295074.039     1688286.477      294520.019
     1688135.356      293901.029
#Sta/Elev= 30
       0 1128.91   128.4 1105.48   147.3 1099.48   182.9 1089.76   224.3 1081.01
   297.3 1069.45   373.1 1055.15   425.6 1049.06   484.2 1043.39   529.7 1036.83
   619.7 1027.39   677.5 1024.17   734.3 1026.34     766 1025.88   791.1 1023.89
   907.7  995.23   946.7  987.15   975.8   983.9   986.8  982.82   990.8  984.28
   999.8  987.95  1031.3 1004.36  1073.9 1024.78  1134.3 1054.88    1216 1103.31
  1266.4 1134.19  1304.6  1156.5    1314  1160.8  1341.2 1170.59  1403.2 1190.25
#Mann= 3 , 0 , 0
       0      .1       0   975.8    .045       0   990.8      .1       0
Bank Sta=975.8,990.8
XS Rating Curve= 0 ,0
Exp/Cntr=0.3,0.1

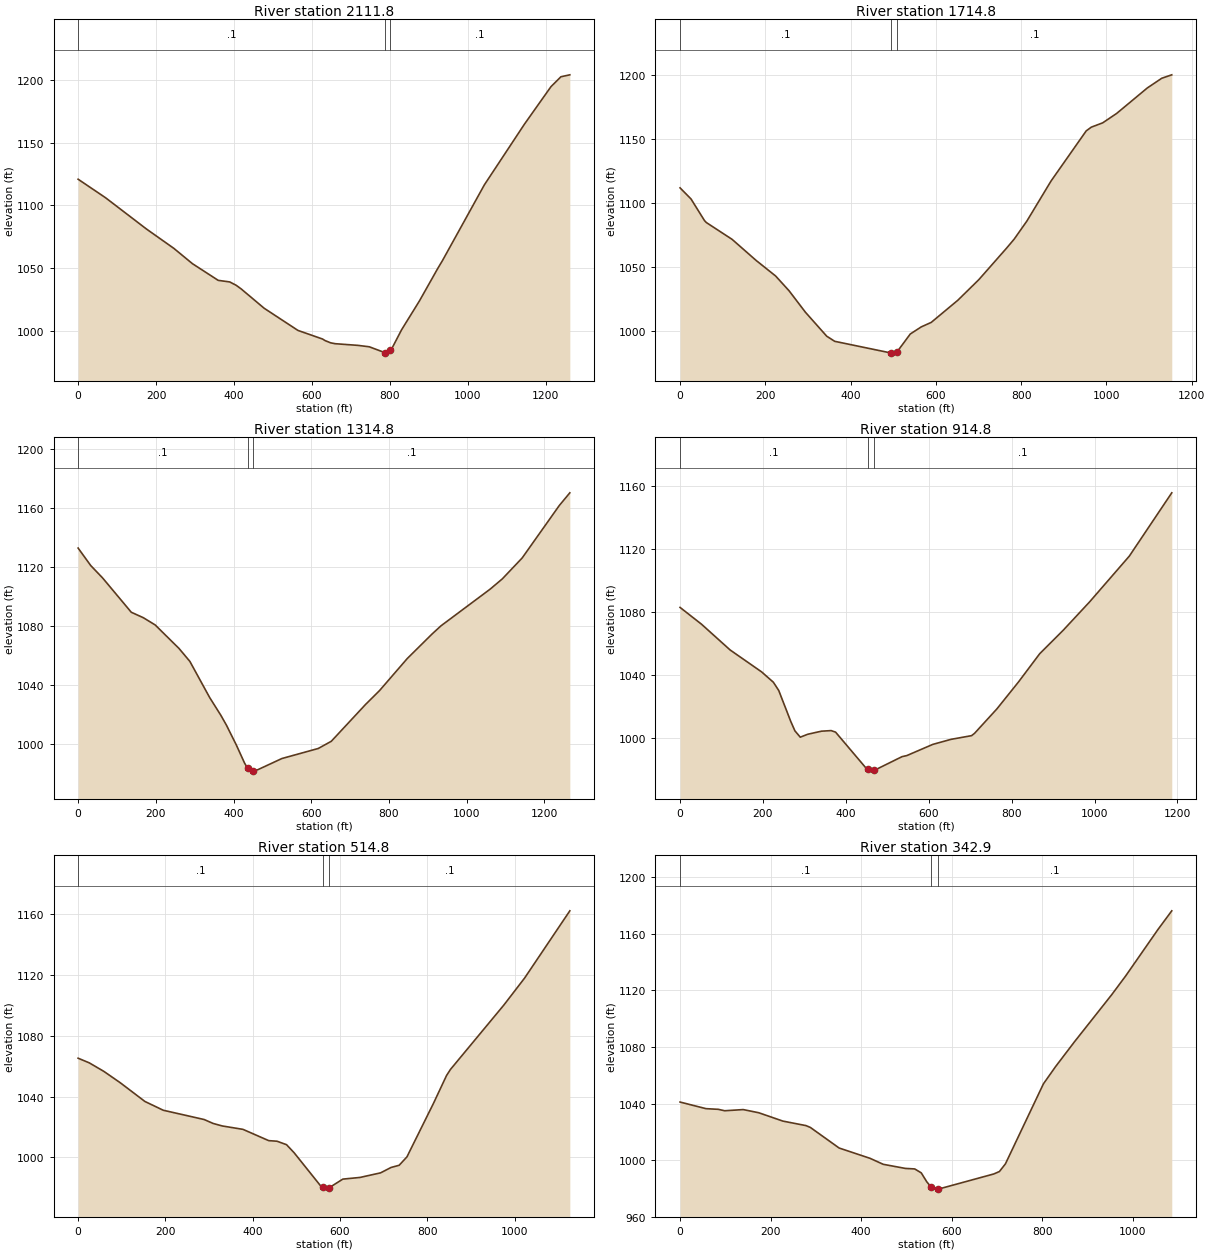
Type RM Length L Ch R = 1 ,2111.8  ,405.004,396.998,385.574
XS GIS Cut Line= 3
     1688897.633      295066.956     1688577.848      294527.188
      1688766.18      293921.155
#Sta/Elev= 30
       0 1120.83    70.4 1106.12   175.8 1081.16   245.5 1065.92   293.6 1053.66
   359.5 1040.45   389.2 1039.18   405.8  1036.5   418.5 1033.63   477.5 1018.27
   564.2 1000.65   627.4   993.8   633.8  992.56   648.2  990.78   659.8  990.09
     718  988.77   747.3  987.64   786.7  983.06   790.5   982.6   801.7  985.01
   804.2  985.65   830.1 1001.12   876.1 1024.14   922.6 1049.68   935.3 1056.27
  1042.6 1116.34  1145.5  1164.6  1213.7 1194.45  1239.2 1202.29    1262 1203.82
#Mann= 3 , 0 , 0
       0      .1       0   786.7    .045       0   801.7      .1       0
Bank Sta=786.7,801.7
XS Rating Curve= 0 ,0
Exp/Cntr=0.3,0.1

Type RM Length L Ch R = 1 ,1714.8  ,414.224,400,393.795
XS GIS Cut Line= 3
     1688985.803      295063.327     1688972.386      294561.696
     1688880.208      293916.836
#Sta/Elev= 30
       0 1111.54    25.7 1102.87    57.4 1085.92    61.8 1084.41   122.1 1071.29
   178.4 1054.83   224.2 1042.65   255.8 1031.07   294.1 1014.31   343.9  995.64
   362.7  991.62   494.3  982.53     496  982.39   509.3  983.54   539.9  997.33
   565.7  1002.9     589 1006.39   651.3 1023.66   700.6 1039.77   765.9 1064.48
   783.5 1071.43   813.5 1085.65   870.1 1116.91   952.5 1156.05   964.5 1158.99
   991.1 1162.33    1024 1169.71  1095.9 1189.63  1129.7 1197.19  1153.2 1199.88
#Mann= 3 , 0 , 0
       0      .1       0   494.3    .045       0   509.3      .1       0
Bank Sta=494.3,509.3
XS Rating Curve= 0 ,0
Exp/Cntr=0.3,0.1

Type RM Length L Ch R = 1 ,1314.8  ,410.401,400,391.775
XS GIS Cut Line= 3
     1689638.476      294981.171     1689357.094      294638.306
     1688972.211      293911.857
#Sta/Elev= 30
       0 1133.05    32.5 1121.21      63 1112.82   136.8 1089.59   167.6 1085.92
   198.3 1080.99   259.6 1065.08   287.6 1056.31   338.6 1031.81   367.2 1019.86
   381.9 1013.04   407.1  999.74   428.2  987.54     436  983.93   448.3  981.96
     451  982.14   462.5  982.92   524.6   990.5   618.1   997.3   651.7 1002.18
   739.7 1027.07   775.9 1036.52     847 1058.16   911.2 1074.87     934 1080.38
  1060.2 1105.15  1091.9 1112.18    1143 1126.35  1238.5 1161.86  1265.7 1170.48
#Mann= 3 , 0 , 0
       0      .1       0     436    .045       0     451      .1       0
Bank Sta=436,451
XS Rating Curve= 0 ,0
Exp/Cntr=0.3,0.1

Type RM Length L Ch R = 1 ,914.8   ,400.705,400,393.509
XS GIS Cut Line= 3
     1690005.644      294503.211     1689585.327      294314.425
     1689037.256      293838.828
#Sta/Elev= 30
       0 1083.03    51.8 1072.34   120.9 1055.95   196.7 1042.04   225.1 1035.46
   238.1 1030.21     267  1010.6   277.1 1004.53   290.1  1000.5   307.8 1002.35
   341.1 1004.32   364.5 1004.69   375.3  1003.7     449  980.76   453.3  980.25
   464.8  978.92   468.3  979.37   535.8  988.15     547  988.79   609.7  995.91
   653.8  999.13   703.4 1001.48   710.5 1002.94   764.5  1018.5   816.7 1035.66
   867.7 1053.57   923.8 1068.32   987.8 1086.44    1084 1115.66  1186.4  1155.9
#Mann= 3 , 0 , 0
       0      .1       0   453.3    .045       0   468.3      .1       0
Bank Sta=453.3,468.3
XS Rating Curve= 0 ,0
Exp/Cntr=0.3,0.1

Type RM Length L Ch R = 1 ,514.8   ,172.356,171.947,169.816
XS GIS Cut Line= 3
     1690129.839      294095.465     1689585.827      293931.771
     1689058.883      293747.083
#Sta/Elev= 30
       0 1065.29    25.6 1062.23    58.9 1056.63    96.5 1049.15   153.1  1036.8
   195.1 1031.03   288.7 1024.93   309.3 1022.34   330.2 1020.69   377.7 1018.45
   436.7 1011.02   455.7 1010.64   477.5 1008.36     495    1003   555.4  981.29
   560.6  980.48   569.4   979.1   575.6   980.1   606.4  985.69   645.7  986.79
     693  989.82     717  993.37   735.5  994.81   753.3 1000.33   814.5 1035.81
     844 1053.88   852.9 1057.86   975.4 1100.31  1022.8 1118.03  1126.5 1162.33
#Mann= 3 , 0 , 0
       0      .1       0   560.6    .045       0   575.6      .1       0
Bank Sta=560.6,575.6
XS Rating Curve= 0 ,0
Exp/Cntr=0.3,0.1

Type RM Length L Ch R = 1 ,342.9   ,289.094,295.329,295.024
XS GIS Cut Line= 3
     1690113.756      293945.397      1689570.34      293757.587
      1689079.15       293617.21
#Sta/Elev= 30
       0 1041.05    57.1 1036.38    84.6 1035.89    98.5 1034.89   139.5 1035.72
   173.9 1033.47     227 1027.58   277.9  1024.4   287.7  1023.1   351.3 1008.53
   419.5 1001.25   448.7  997.01   497.5  994.11   518.2  993.74   532.6  990.96
   545.1   984.5   554.5  980.95   557.7   979.8   569.5  979.52   570.3  979.46
   692.7  990.18   705.2   991.9   718.5  997.33   802.4 1053.93   829.4 1066.19
   870.8  1083.6   953.1 1116.93   984.4 1130.41  1055.2 1163.03  1085.8 1176.29
#Mann= 3 , 0 , 0
       0      .1       0   554.5    .045       0   569.5      .1       0
Bank Sta=554.5,569.5
XS Rating Curve= 0 ,0
Exp/Cntr=0.3,0.1

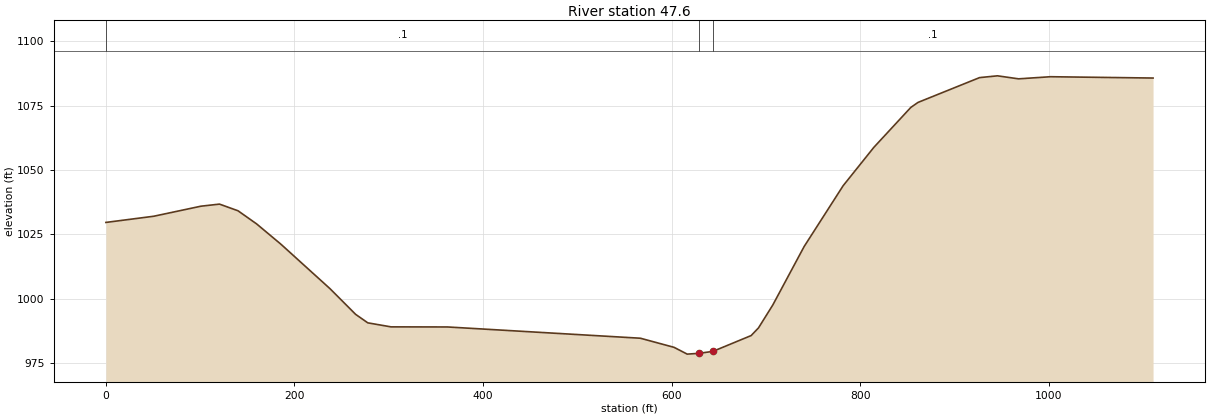
Type RM Length L Ch R = 1 ,47.6    ,50.064,47.565,52.335
XS GIS Cut Line= 3
     1690126.487      293867.733     1689614.943      293480.207
     1689158.574      293372.464
#Sta/Elev= 30
       0 1029.68    50.7 1032.08   100.8 1035.98   120.5 1036.79   140.1 1034.21
   159.8 1029.13   185.7 1021.21   237.7 1003.97   264.9     994   277.8  990.71
   302.4  989.15   362.4  989.11   566.9  984.74   602.6  981.21   616.6  978.57
   628.8  978.87   643.8  979.63   684.4  985.77   692.2  988.75   707.4  997.66
   740.6 1020.32     782 1043.94   814.6 1058.84   853.8 1074.33   861.4 1076.26
   926.7 1085.89   945.7 1086.58   968.1 1085.41  1001.9 1086.23  1110.7 1085.72
#Mann= 3 , 0 , 0
       0      .1       0   628.8    .045       0   643.8      .1       0
Bank Sta=628.8,643.8
XS Rating Curve= 0 ,0
Exp/Cntr=0.3,0.1

Chan Stop Cuts=-1
Use User Specified Reach Order=0